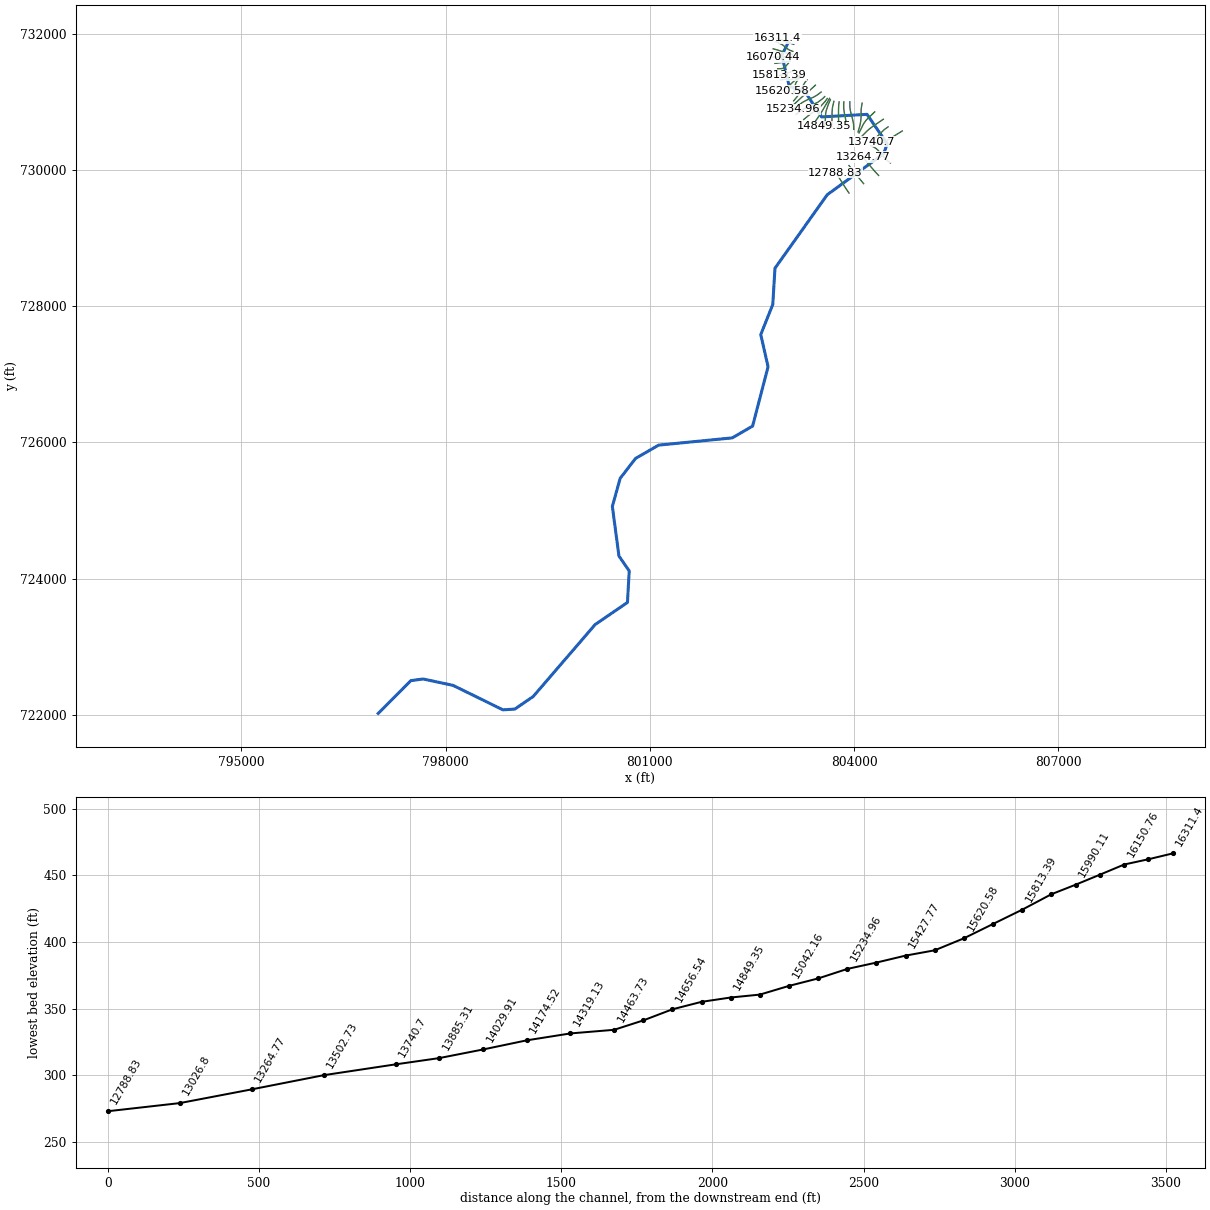
--- 6817_ras.prj (project) ---

Proj Title=6817
Current Plan=p01
Default Exp/Contr=0.3,0.1
English Units
Geom File=g01
Flow File=f01
Plan File=p01
Y Axis Title=Elevation
X Axis Title(PF)=Main Channel Distance
X Axis Title(XS)=Station
BEGIN DESCRIPTION:
RFD model 6817 exported to HEC-RAS
END DESCRIPTION:

--- 6817_ras.p01 (plan) ---

Plan Title=Plan 01
Program Version=4.10
Short Identifier=Plan 01
Geom File=g01
Flow File=f01
Subcritical Flow
Calc Critical at every XS
Secant Critical Depth

--- 6817_ras.f01 (steady flow) ---

Flow Title=Flow 01
Program Version=5.01
Number of Profiles= 6
Profile Names=10yr,25yr,50yr,100yr,100plus,500yr
River Rch & RM=6817,57, 16311.4
 1519.85  2491.6 3423.95 4289.65 6262.89 8132.39
River Rch & RM=6817,57,16231.08
 1521.23  2494.1 3427.61 4294.47 6269.93 8141.26
River Rch & RM=6817,57,16150.76
 1524.13 2499.38 3435.34 4304.69 6284.85  8160.1
River Rch & RM=6817,57,15990.11
 1525.34 2501.57 3438.54  4308.9    6291 8167.86
River Rch & RM=6817,57,15909.79
 1531.48 2512.74 3454.88  4330.5 6322.53 8207.69
River Rch & RM=6817,57,15813.39
 1532.86 2515.23 3458.53 4335.31 6329.56 8216.54
River Rch & RM=6817,57,15620.58
 1534.74 2518.64 3463.52 4341.91 6339.18 8228.69
River Rch & RM=6817,57,15524.18
 1535.75 2520.49 3466.23 4345.49 6344.42 8235.31
River Rch & RM=6817,57,15427.77
 1537.12 2522.98 3469.86 4350.29 6351.42 8244.14
River Rch & RM=6817,57,15234.96
 1577.62 2597.01 3578.57 4494.34 6561.73 8510.62
River Rch & RM=6817,57,15138.56
  1586.4 2612.85 3601.68 4524.79  6606.2 8566.13
River Rch & RM=6817,57,15042.16
 1589.32 2618.23  3609.6 4535.33 6621.58 8585.68
River Rch & RM=6817,57,14945.75
 1590.94 2621.22 3614.01 4541.18 6630.12 8596.54
River Rch & RM=6817,57,14752.94
 1592.75 2624.52 3618.87 4547.63 6639.54 8608.48
River Rch & RM=6817,57,14656.54
 1593.88 2626.61 3621.95 4551.73 6645.52 8616.07
River Rch & RM=6817,57,14560.14
 1594.86 2628.41 3624.59 4555.23 6650.64 8622.58
River Rch & RM=6817,57,14463.73
 1595.51  2629.6 3626.35 4557.57 6654.06 8626.92
River Rch & RM=6817,57,14319.13
 1601.01 2639.52 3640.82 4576.64 6681.89 8661.58
River Rch & RM=6817,57,14174.52
 1601.52 2640.45 3642.17 4578.41 6684.48 8664.82
River Rch & RM=6817,57,14029.91
 2212.23 3645.84 5029.07 6318.71 9225.3111409.45
River Rch & RM=6817,57,13885.31
  2213.5 3648.14 5032.44 6323.15  9231.811417.22
River Rch & RM=6817,57, 13740.7
 2214.44 3649.86 5034.96 6326.49 9236.6711423.04
River Rch & RM=6817,57,13502.73
 2811.35 4655.18 6442.58 8116.16 11849.614226.06
River Rch & RM=6817,57,13264.77
 2814.06 4660.09 6449.78 8125.6711863.4814242.09
River Rch & RM=6817,57, 13026.8
 2817.47 4666.31  6458.9 8137.7511881.1214262.56
River Rch & RM=6817,57,12788.83
  2819.2 4669.49  6463.6    814411890.2414273.23
River Rch & RM=6817,57,12550.86
 2862.07 4747.55 6578.12 8295.5812111.5514529.41
River Rch & RM=6817,57,12312.89
 2864.46 4751.98 6584.68 8304.3312124.3314544.42
River Rch & RM=6817,57,12074.92
 2866.57 4755.89 6590.47 8312.05 12135.614557.66
River Rch & RM=6817,57,11836.96
 2872.52 4766.87 6606.71 8333.6912167.1914594.72
River Rch & RM=6817,57,11598.99
 2878.59  4778.1 6623.32 8355.8312199.5214632.61
River Rch & RM=6817,57,11361.02
 2991.06 4984.62 6927.87 8760.7212790.6615319.59
River Rch & RM=6817,57,11123.05
 2994.11 4990.27 6936.24 8771.8912806.9615338.62
River Rch & RM=6817,57,10885.08
 2997.98 4997.44 6946.86 8786.0712827.6615362.82
River Rch & RM=6817,57,10647.11
 3006.73 5013.62 6970.82 8818.0312874.3215417.23
River Rch & RM=6817,57,10371.31
 3008.12 5016.19 6974.62  8823.112881.7315425.86
River Rch & RM=6817,57, 10143.8
 3010.63 5020.83 6981.48 8832.2412895.0715441.38
River Rch & RM=6817,57,9916.298
 3021.19 5040.51 7010.75 8871.4312952.29 15508.6
River Rch & RM=6817,57,9688.793
 3250.44  5448.1 7601.07 9644.5514081.0516762.41
River Rch & RM=6817,57,9461.289
 3279.22 5500.37 7677.72 9746.0214229.1816929.94
River Rch & RM=6817,57,9233.784
 3289.96 5520.02 7706.67 9784.4914285.3616993.94
River Rch & RM=6817,57, 9006.28
 3368.97 5667.31 7925.9310078.3914714.4517491.13
River Rch & RM=6817,57,8778.775
 3369.79 5668.81 7928.1510081.3514718.7717496.06
River Rch & RM=6817,57,8279.022
 3373.04 5674.88  7937.210093.4814736.4817516.58
River Rch & RM=6817,57,7779.269
 3375.99 5680.42 7945.47 10104.614752.7117535.46
River Rch & RM=6817,57,7279.517
 3441.09 5801.04 8124.4610343.9215102.13 17936.5
River Rch & RM=6817,57,6779.764
 3447.18 5812.55 8141.7410367.2515136.1917976.33
River Rch & RM=6817,57,6339.192
 3458.32 5833.65 8173.4210410.0215198.6318049.39
River Rch & RM=6817,57,5668.416
12491.1521056.8329523.2137549.9154822.8754065.73
River Rch & RM=6817,57,5280.506
12492.2221058.92 29526.437554.2654829.2254072.05
River Rch & RM=6817,57, 5002.58
12493.6621061.7129530.6537560.0654837.6954080.49
River Rch & RM=6817,57,    4281
12519.5521111.4929606.1337662.5654987.3454228.02
Boundary for River Rch & Prof#=6817,57,1
Up Type= 0
Dn Type= 2
Boundary for River Rch & Prof#=6817,57,2
Up Type= 0
Dn Type= 2
Boundary for River Rch & Prof#=6817,57,2
Up Type= 0
Dn Type= 2
Boundary for River Rch & Prof#=6817,57,2
Up Type= 0
Dn Type= 2
Boundary for River Rch & Prof#=6817,57,2
Up Type= 0
Dn Type= 2
Boundary for River Rch & Prof#=6817,57,2
Up Type= 0
Dn Type= 2

--- 6817_ras.g01 (geometry) ---

Geom Title=6817
Program Version=4.10

River Reach=6817,57
Reach XY= 30
803032.894840032731868.636780114802937.573667257731682.314578491
803046.786546022731226.662458133 803282.77270055731141.500447912
803521.701372207  730776.5272857804189.483945638730814.217306273
804486.132883339730381.039150404804434.718284757730237.866310612
 803605.33671683729634.772514112802837.425226569 728556.15060771
802805.389921669728024.787465079 802628.78731561727582.409256842
802736.058283687727110.256491418802508.950555086726239.421757946
802209.624169826726066.467931181801128.774499328725960.124136426
800788.679598183725764.254732157800563.506678582725472.149261734
800448.923345207725060.690928409 800545.81809938724332.883806729
800696.859766037724114.133806719800670.502798351 723651.20286934
800196.859766065723327.675473429 799286.50680256722271.346272823
799016.284507306722086.561846299798841.297887981722075.759227057
798108.318099381722434.880334516797668.663581938722528.439932939
797489.695975901722504.122291654797010.178867281722023.637192484

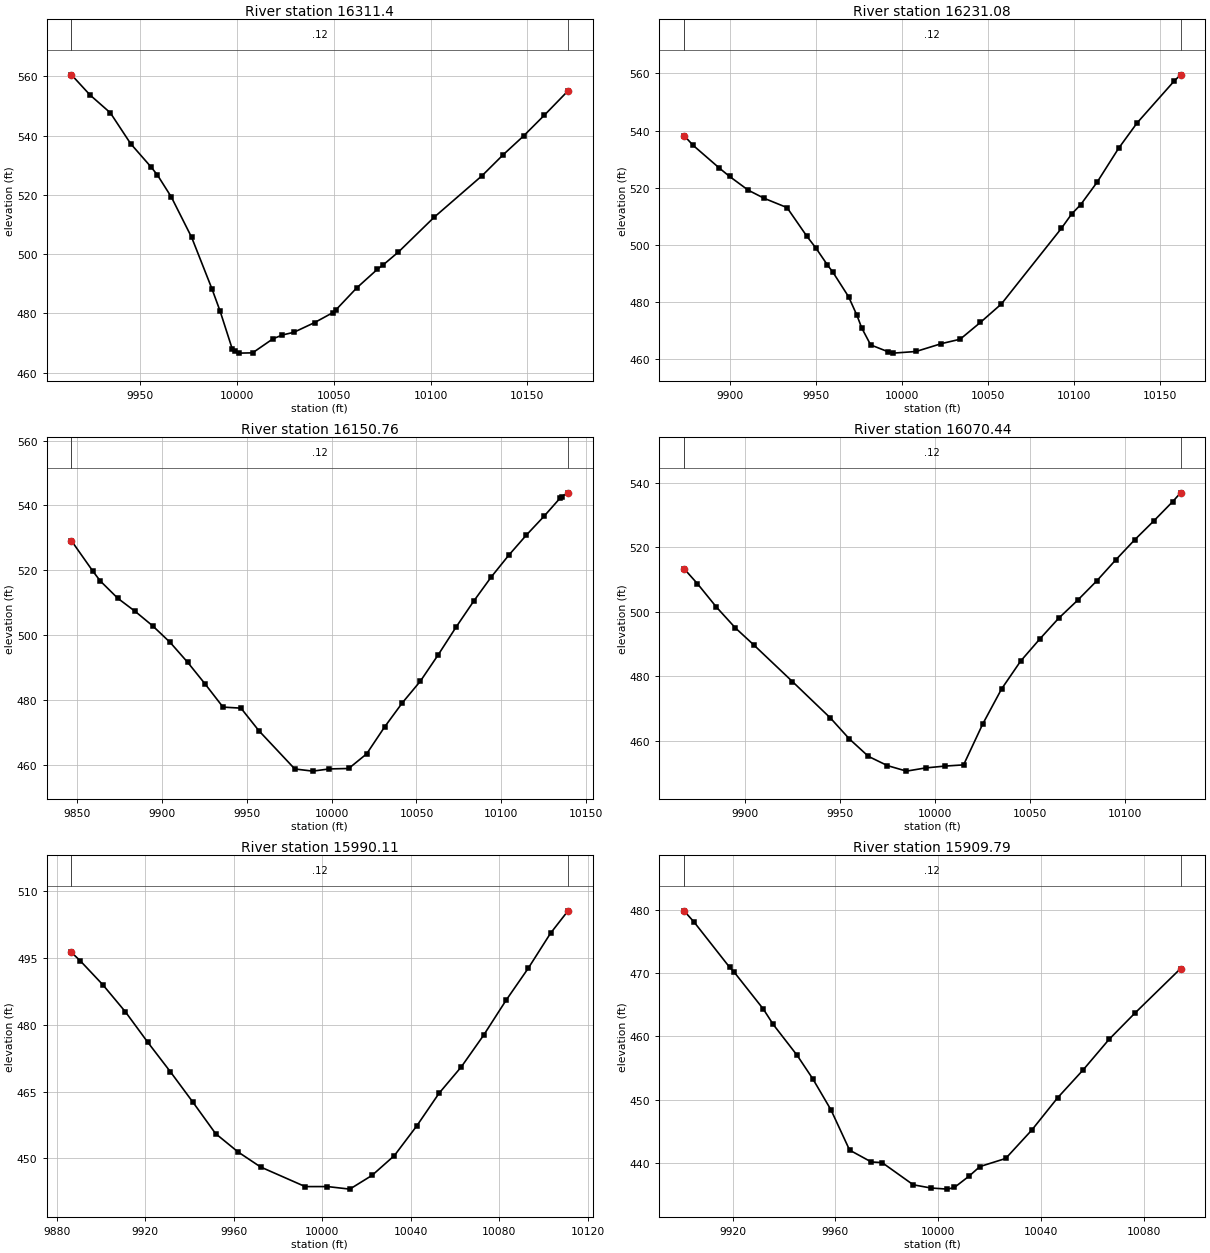
Type RM Length L Ch R = 1 , 16311.4,80.321800,80.321800,80.321800
XS GIS Cut Line= 6
803114.103192469731841.288899948803033.591328222731867.405965668
803031.664025586731867.940291924803013.648684412731873.659643214
802905.066616999731918.668220267802873.310359728731929.711011185
#Sta/Elev= 30
9914.358560.55779923.928553.75619934.441547.72159944.954537.28959955.467529.4432
9958.794526.7104 9965.98 519.2749976.493505.63889987.006488.21619991.203480.7138
9997.519467.8588    9999 467.183   10001466.553310007.99466.649610018.48471.3748
 10023.4472.685610029.26473.574810040.09476.888610049.52480.247110050.91481.0611
10061.74 488.53210072.56494.911510075.63496.434610083.39500.712310101.75512.3948
10126.69526.529710137.51533.5472 10148.1539.921210158.69546.833310171.06555.1467
#Mann= 3 , 0 , 0
9914.358    0.12       09914.358    0.12       010171.06    0.12       0
#XS Ineff= 2 , 0
       0                               0
Bank Sta=9914.358,10171.06
Exp/Cntr=0.3,0.1

Type RM Length L Ch R = 1 ,16231.08,80.321700,80.321700,80.321700
XS GIS Cut Line= 6
803099.916589468 731737.78328723803056.447567258731754.512443307
803030.426803986 731769.28294799802955.583987447731828.622902168
802927.045470309731846.237060292802851.683794355731880.185246482
#Sta/Elev= 30
9873.422538.26849878.588534.90729893.922526.89949899.819523.99399910.726519.1624
9920.054516.29969933.218513.08499944.716503.08379949.975498.95129956.662493.0483
 9959.76490.58269968.984 481.898 9973.84475.3831 9976.58471.02019981.789465.0636
9992.027462.63419994.909462.181410008.11462.751310022.93465.505710033.76467.0431
10045.55472.9344 10057.7479.360810092.59505.838910098.52510.829210103.79514.1209
10113.26521.911310125.76 533.77910136.58542.731210158.23557.4449 10161.8559.5165
#Mann= 3 , 0 , 0
9873.422    0.12       09873.422    0.12       0 10161.8    0.12       0
#XS Ineff= 2 , 0
       0                               0
Bank Sta=9873.422,10161.8
Exp/Cntr=0.3,0.1

Type RM Length L Ch R = 1 ,16150.76,80.321800,80.321800,80.321800
XS GIS Cut Line= 6
803091.717055877731693.710794149803079.382220196731695.480102516
 803013.29063456731711.800407031802943.551023536731735.893679209
802884.494281121731755.990096612802811.318538987731776.196381553
#Sta/Elev= 30
9846.675529.11099859.136 519.8749863.649516.7535 9873.95511.4315 9884.25507.3748
9894.551502.92719904.851497.82549915.151491.70989925.452485.02889935.979477.9259
9946.553477.61149957.127470.65239978.275 458.8859988.849458.22129998.593458.8981
10010.03459.0303 10020.6 463.52310031.16471.786310041.72 479.29610052.29485.9173
10062.85 494.07310073.23502.482710083.61510.466610093.98517.940210104.35524.6703
10114.73 530.874 10125.1536.6382 10134.8542.367110135.48542.7518 10139.3543.8926
#Mann= 3 , 0 , 0
9846.675    0.12       09846.675    0.12       0 10139.3    0.12       0
#XS Ineff= 2 , 0
       0                               0
Bank Sta=9846.675,10139.3
Exp/Cntr=0.3,0.1

Type RM Length L Ch R = 1 ,16070.44,80.321700,80.321700,80.321700
XS GIS Cut Line= 6
803072.021753752731659.007518035802994.802644712731659.532891779
802940.983415951 731656.13034514802908.876751029731653.726355321
802865.157981529731652.651703407802810.818958629731653.740928619
#Sta/Elev= 26
9867.852513.38939874.874508.75419884.875501.48769894.875495.01339904.875489.5715
9924.875478.39339944.876467.08949954.896460.57689964.916455.17079974.935452.3041
9984.955450.59249994.975451.5796   10005452.146410015.03452.533410025.06465.1614
10035.07476.128110045.08484.735110055.08 491.53510065.08498.011610075.09503.6128
10085.09509.579710095.09516.092810105.09522.339910115.09528.1564 10125.1534.1834
10129.28536.9262
#Mann= 3 , 0 , 0
9867.852    0.12       09867.852    0.12       010129.28    0.12       0
#XS Ineff= 2 , 0
       0                               0
Bank Sta=9867.852,10129.28
Exp/Cntr=0.3,0.1

Type RM Length L Ch R = 1 ,15990.11,80.321800,80.321800,80.321800
XS GIS Cut Line= 5
803058.914720371  731595.4061689802978.542207975731579.903091686
802948.331607112731576.145415008  802946.3399941731575.962446128
802837.158371448731562.474450142
#Sta/Elev= 23
9886.703 496.2449890.689494.35329900.874488.97589911.058482.90459921.242476.0138
9931.427469.40689941.611462.56759951.795455.5447 9961.98451.41289972.126448.0464
 9992.28443.639610002.35443.644310012.43443.0707 10022.5446.170210032.58450.6156
10042.65457.252510052.73464.599210062.81470.543610072.88477.647210082.96485.4548
10093.03492.683110103.11500.561610111.01505.5964
#Mann= 3 , 0 , 0
9886.703    0.12       09886.703    0.12       010111.01    0.12       0
#XS Ineff= 2 , 0
       0                               0
Bank Sta=9886.703,10111.01
Exp/Cntr=0.3,0.1

Type RM Length L Ch R = 1 ,15909.79,96.404000,96.404000,96.404000
XS GIS Cut Line= 6
803037.598177462731568.450788171802998.627589226731522.985101923
802958.418578804731491.399466977802954.905258298731489.140117601
 802930.05120039731484.790657461802877.112341374  731483.9762135
#Sta/Elev= 25
9901.052479.83499905.044478.01519918.767 470.936 9920.41470.23849931.938464.3192
9935.776461.89439945.109457.01099951.142453.3389 9958.28448.40099965.521442.0598
9973.977440.18859978.168440.09129990.312436.58269997.161 436.07810003.62435.8995
10006.33436.161910012.07437.959510016.25439.4574 10026.3440.739610036.45445.2128
10046.53450.319910056.53454.749210066.53459.527110076.53463.646710094.42470.7199
#Mann= 3 , 0 , 0
9901.052    0.12       09901.052    0.12       010094.42    0.12       0
#XS Ineff= 2 , 0
       0                               0
Bank Sta=9901.052,10094.42
Exp/Cntr=0.3,0.1

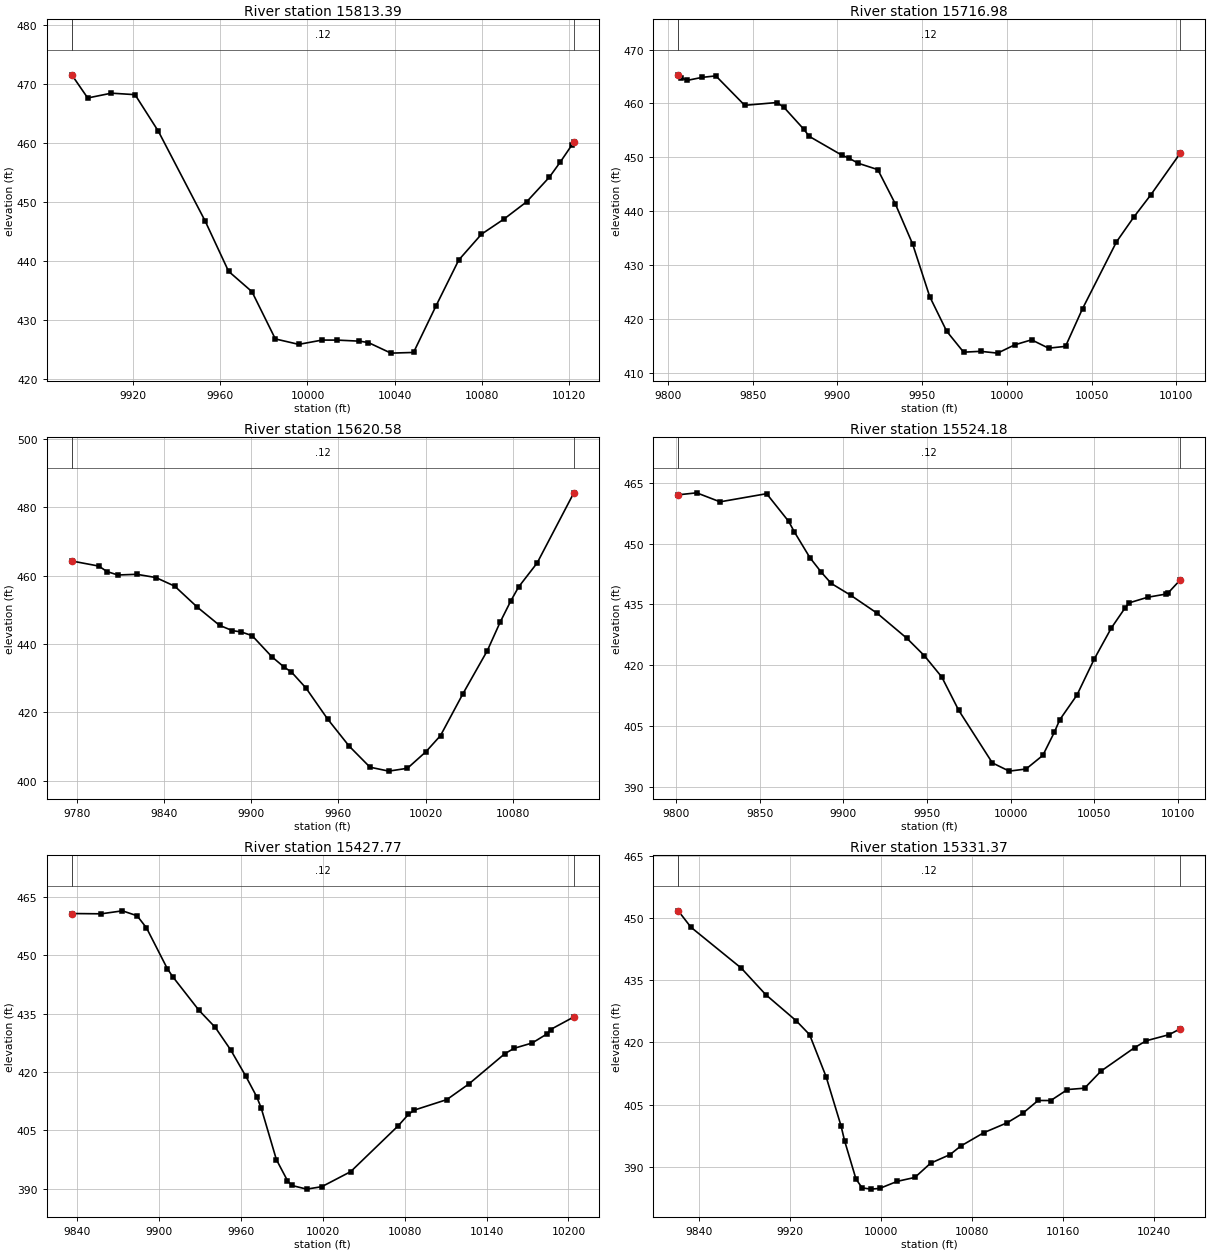
Type RM Length L Ch R = 1 ,15813.39,96.404000,96.404000,96.404000
XS GIS Cut Line= 6
803121.729623612731460.257367189803095.703144741731449.116160914
803020.350413395731419.478464904802998.932220775 731411.45843855
802910.174327738731386.312524859802904.103968654731384.737632896
#Sta/Elev= 25
9891.717471.56239899.037467.63199909.915468.44959920.783468.19599931.527461.9641
9953.014446.73559963.757438.21519974.501434.75399985.245426.73339995.988425.8109
10006.71426.540610013.77426.534310023.87426.357510027.96426.123110038.35424.3252
10048.74424.439710059.14432.400210069.53440.141810079.93444.505910090.32447.0894
10100.71450.012410111.11454.174810116.12456.738610121.35459.579410122.39460.2359
#Mann= 3 , 0 , 0
9891.717    0.12       09891.717    0.12       010122.39    0.12       0
#XS Ineff= 2 , 0
       0                               0
Bank Sta=9891.717,10122.39
Exp/Cntr=0.3,0.1

Type RM Length L Ch R = 1 ,15716.98,96.404000,96.404000,96.404000
XS GIS Cut Line= 6
803196.427962235731388.037758162803132.239971038731344.935023995
 803085.48380526731326.686310426803045.619093284731323.476610953
802982.281801647731327.376790382802917.998846309731318.568979113
#Sta/Elev= 30
9806.071 465.3149807.836464.79219811.241464.27549820.194464.84269828.261465.1168
9845.291459.65139864.305460.16849868.439459.27599880.197455.19299883.318453.8931
9902.447450.41839907.048449.78889912.175448.89649923.834447.70149934.252441.2774
9944.355433.89719954.458424.11189964.459417.68499974.462  413.799984.496413.9457
 9994.53413.612810004.55415.146310014.56 416.08410024.58 414.53410034.59 414.869
10044.61421.861610064.66434.282310074.78438.842510084.91443.016810102.32450.7655
#Mann= 3 , 0 , 0
9806.071    0.12       09806.071    0.12       010102.32    0.12       0
#XS Ineff= 2 , 0
       0                               0
Bank Sta=9806.071,10102.32
Exp/Cntr=0.3,0.1

Type RM Length L Ch R = 1 ,15620.58,96.404000,96.404000,96.404000
XS GIS Cut Line= 6
803209.266996402 731380.52222597 803136.35270422731319.332946391
803054.979250838731245.329945799 803040.12777769731233.182532793
 802966.44743981731174.841944356802944.486654813731159.075095856
#Sta/Elev= 30
9776.635464.3029 9795.26462.81549800.781461.22739808.315460.20559821.369460.4115
9834.424459.4685 9847.45456.94399863.006450.79839878.262445.49239887.167443.9311
9893.125443.56129900.684442.47589914.201436.32719922.851433.21929927.718431.8479
9937.715427.16999952.578418.11629967.441 410.1679981.785403.99999994.702402.8472
10007.54403.6794 10020.3408.535910030.29413.236210045.81425.547410062.51438.0913
10071.32446.406510078.62452.606210084.07456.737810096.76463.718610122.02484.2395
#Mann= 3 , 0 , 0
9776.635    0.12       09776.635    0.12       010122.02    0.12       0
#XS Ineff= 2 , 0
       0                               0
Bank Sta=9776.635,10122.02
Exp/Cntr=0.3,0.1

Type RM Length L Ch R = 1 ,15524.18,96.404000,96.404000,96.404000
XS GIS Cut Line= 6
803223.049543501731372.454393524803182.136852031731331.291356103
803147.277523087731281.524581516803134.598787489731245.327553294
803118.360678418731145.268592344803102.245148668731106.962783329
#Sta/Elev= 30
9801.131462.0613 9812.17462.55019826.149460.32759854.016 462.3379867.201455.5091
9870.698 452.8499879.945446.53239886.831442.90669892.688440.1856 9904.42437.2464
9920.079432.8522    9938426.62879948.459422.32619958.836417.08829968.923408.8993
9989.097395.88939999.183393.857610009.25 394.38110019.31 397.74810026.16403.4324
10029.45406.547310039.73412.637410050.01421.4776 10060.3 429.19210068.68434.2428
10071.15435.4145   10082436.770810092.85437.548810094.46437.921510101.57441.0728
#Mann= 3 , 0 , 0
9801.131    0.12       09801.131    0.12       010101.57    0.12       0
#XS Ineff= 2 , 0
       0                               0
Bank Sta=9801.131,10101.57
Exp/Cntr=0.3,0.1

Type RM Length L Ch R = 1 ,15427.77,96.404000,96.404000,96.404000
XS GIS Cut Line= 6
 803307.83303389 731321.76930432803278.572290063731283.939575404
803246.649098963731231.488398552803186.492932737731111.014274746
803160.987675816731071.362560675803111.842101067731012.335933171
#Sta/Elev= 30
9836.034460.7515 9857.57 460.677 9873.16461.44639883.882460.17979890.753457.0858
9906.054446.58259909.987444.51949929.222435.87549941.173431.47669952.524425.6645
9963.682 418.8539971.542413.6517 9974.84410.75789985.999397.45629994.082392.0791
9997.157390.826910008.21389.8737 10019.3390.505710040.43394.368610075.44406.2172
10082.73 409.08810087.12410.2057 10110.9412.895510127.11416.934510153.41 424.705
10160.32426.102310173.45427.458210184.35429.794910186.92430.921710203.99434.1522
#Mann= 3 , 0 , 0
9836.034    0.12       09836.034    0.12       010203.99    0.12       0
#XS Ineff= 2 , 0
       0                               0
Bank Sta=9836.034,10203.99
Exp/Cntr=0.3,0.1

Type RM Length L Ch R = 1 ,15331.37,96.404000,96.404000,96.404000
XS GIS Cut Line= 6
803431.590374701 731242.55980475803364.837922023731181.074833082
803299.188826794731124.993289238803247.850850039731081.536048908
803139.299305425730980.977284624803102.496778352730948.398582992
#Sta/Elev= 30
9821.904451.73469833.063447.78439877.344437.92289898.842431.53299925.597425.2463
9937.406421.88839951.901411.77169965.053399.89939968.198396.28549978.205387.0812
9983.594 384.9519991.357384.6549 9998.99384.823710014.52386.534810029.99387.4737
10043.78390.901810060.91392.979310070.15395.0059 10090.6398.260610111.04400.6378
10124.67402.897410138.31406.021910149.45 406.00610164.17408.6608 10179.2408.9853
 10193.6413.092610223.25418.773210233.33420.408410253.43421.882310263.38423.3007
#Mann= 3 , 0 , 0
9821.904    0.12       09821.904    0.12       010263.38    0.12       0
#XS Ineff= 2 , 0
       0                               0
Bank Sta=9821.904,10263.38
Exp/Cntr=0.3,0.1

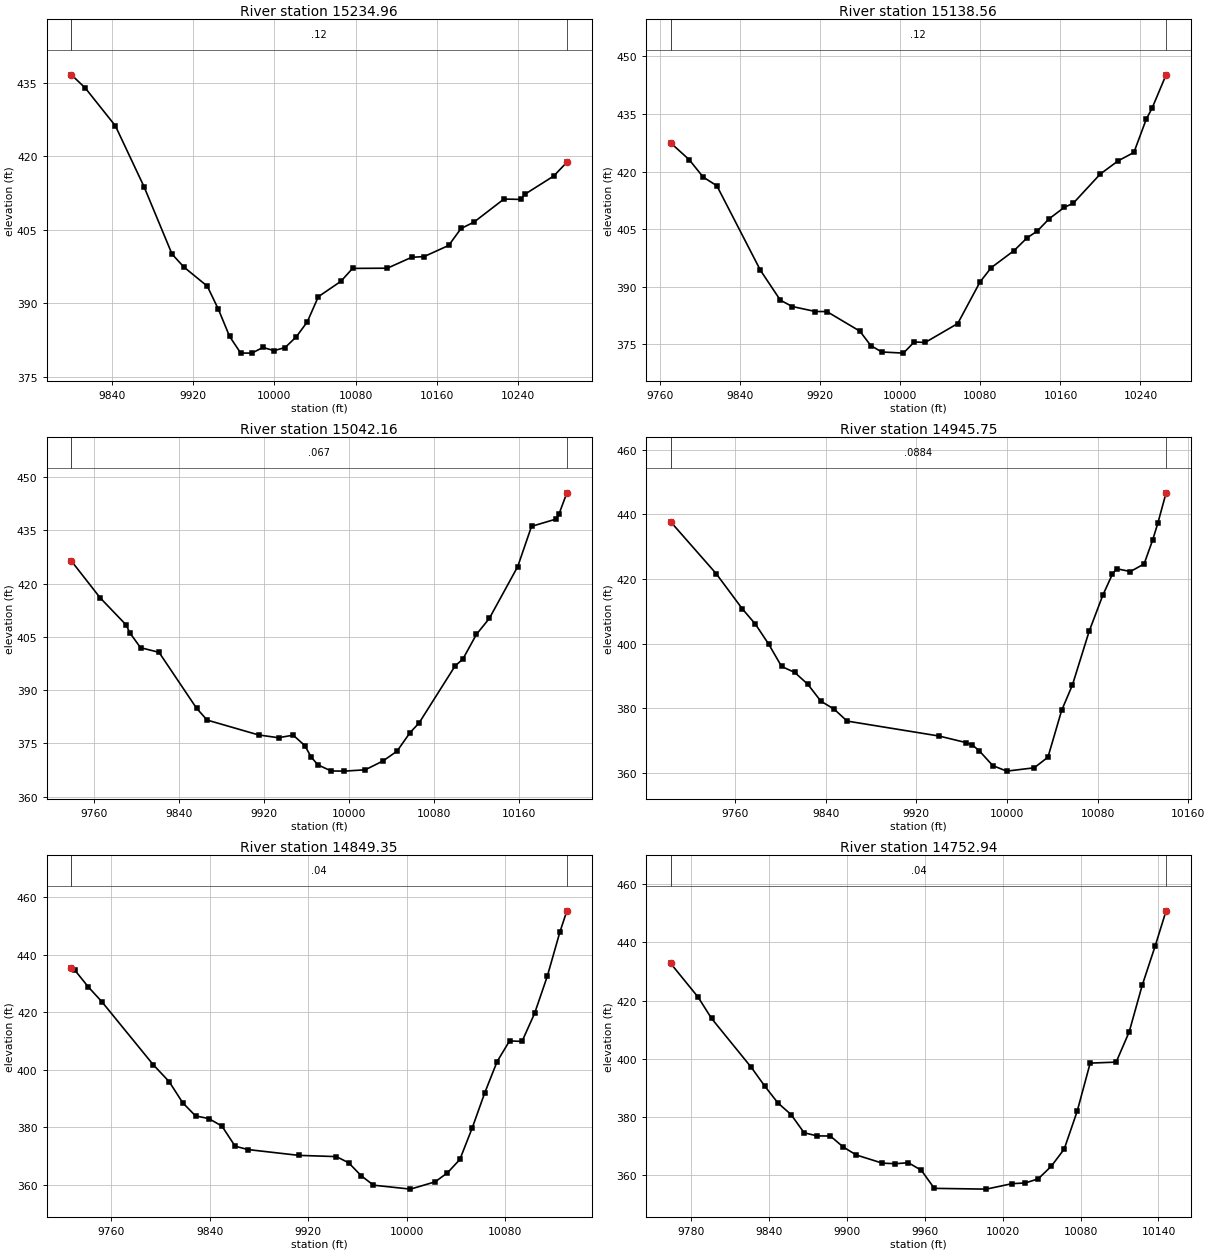
Type RM Length L Ch R = 1 ,15234.96,96.404100,96.404100,96.404100
XS GIS Cut Line= 6
803515.471535457731141.884986792803458.797666244731098.500798926
803405.332717648731067.334945812803294.359420738731018.655394647
803240.332642746730988.968120038803102.694075329 730887.06480566
#Sta/Elev= 30
9800.453436.5795 9814.06433.89189843.705426.17789871.865413.7947 9899.41400.0589
9910.985397.43429934.114393.51759945.063388.79599956.011383.2994 9966.96379.8986
9977.908379.87969988.857381.03479999.801380.388910010.69381.018410021.57383.1864
10032.46386.236110043.35391.374810065.61394.519510077.02397.142610111.25397.1839
10135.19399.404910147.33399.543610171.61401.821810183.75405.274710196.41406.5611
10225.99411.273310242.31411.195610247.02412.307710274.95415.9634 10287.9418.7751
#Mann= 3 , 0 , 0
9800.453    0.12       09800.453    0.12       0 10287.9    0.12       0
#XS Ineff= 2 , 0
       0                               0
Bank Sta=9800.453,10287.9
Exp/Cntr=0.3,0.1

Type RM Length L Ch R = 1 ,15138.56,96.404000,96.404000,96.404000
XS GIS Cut Line= 6
803568.046280483731074.523594739803537.837660381731044.528390407
803465.215801052730990.533995584803290.634171364730910.381445772
803253.504127316730889.045638151803149.091790449730816.657460341
#Sta/Elev= 30
9770.281427.46389788.802 423.0989802.819418.55699816.497416.29739860.025394.3132
 9879.97386.52079891.848384.87489915.092383.56719926.468383.55949959.467378.4604
9970.364374.71219981.262373.044910003.02372.740110013.88375.660510024.75375.5076
10057.33380.448110079.63391.279410090.82394.987310113.74399.449810126.58 402.733
 10136.8404.499710148.76407.721210163.78410.666710172.82 411.75210199.75419.3363
10217.73 422.79410233.43424.969710245.85433.663710251.54436.459710265.61445.1715
#Mann= 3 , 0 , 0
9770.281    0.12       09770.281    0.12       010265.61    0.12       0
#XS Ineff= 2 , 0
       0                               0
Bank Sta=9770.281,10265.61
Exp/Cntr=0.3,0.1

Type RM Length L Ch R = 1 ,15042.16,96.403900,96.403900,96.403900
XS GIS Cut Line= 6
 803605.52947263731046.858529388803572.827401086731002.552289455
803505.738944753730928.908433059803480.492680935730907.172072863
803332.475569196730798.826377528803259.285826742 730738.58641312
#Sta/Elev= 30
9739.141426.34189766.308415.9407 9790.55408.37569794.209406.07979804.169401.9412
9821.553400.63529856.921384.86529866.855381.54239915.223377.3522 9934.02376.5673
9947.865377.29089958.782374.34899964.826371.09289971.163368.90859983.544 367.206
9995.925367.153510015.65367.526410032.56370.050210045.52372.771310057.92378.0273
10066.39380.751410100.21396.789710107.52398.719210120.34405.709710132.41410.1715
10159.19424.806910172.14436.125310195.35438.191210198.05439.632410205.45445.5784
#Mann= 3 , 0 , 0
9739.141   0.067       09739.141   0.067       010205.45   0.067       0
#XS Ineff= 2 , 0
       0                               0
Bank Sta=9739.141,10205.45
Exp/Cntr=0.3,0.1

Type RM Length L Ch R = 1 ,14945.75,96.404100,96.404100,96.404100
XS GIS Cut Line= 6
803639.685728967731049.751532406803530.872134328730862.071659908
803499.279041678730810.994727641803488.313242376730795.597272545
803487.104153365730794.004129812803408.236807249730678.991272962
#Sta/Elev= 30
9703.096437.67639743.266 421.6579766.384410.76679777.944406.02689789.503399.9446
9801.062392.95429812.621391.1147 9824.18387.46089835.739382.21659847.299379.8062
9858.858376.08179940.112 371.4559963.629369.45049969.221368.75339975.387366.9535
9987.473362.3215 9999.75360.612910024.04  361.6410036.17364.919410048.29379.4155
10057.77387.224410072.54403.829910084.67415.031610093.13 421.53710096.79423.1746
10108.92422.284210121.05424.6435 10128.5431.929610133.17  437.2310140.46446.6181
#Mann= 3 , 0 , 0
9703.096  0.0884       09703.096  0.0884       010140.46  0.0884       0
#XS Ineff= 2 , 0
       0                               0
Bank Sta=9703.096,10140.46
Exp/Cntr=0.3,0.1

Type RM Length L Ch R = 1 ,14849.35,96.404000,96.404000,96.404000
XS GIS Cut Line= 6
803651.215981126731027.399460951803623.596576642730967.109588744
803588.298042287730863.836343173803578.970279804730796.693917968
803577.127707706730730.396191375803561.877547198730639.448154226
#Sta/Elev= 30
9727.905435.42539730.544434.61529741.543428.75489752.543423.6046 9794.22401.7139
9807.189395.80599818.231388.44539828.609383.88669839.319382.96829850.029380.3525
9860.691373.37189871.083372.1923 9912.45370.16649942.905369.74179952.945367.5678
9962.985363.10339973.019359.808410003.03358.434710023.04360.975910033.05364.1105
 10043.1368.745510053.18379.765210063.27391.878310073.35402.800610083.44409.9691
10093.53409.778210103.76 419.54910114.02432.399210124.27 447.81610129.96455.1872
#Mann= 3 , 0 , 0
9727.905    0.04       09727.905    0.04       010129.96    0.04       0
#XS Ineff= 2 , 0
       0                               0
Bank Sta=9727.905,10129.96
Exp/Cntr=0.3,0.1

Type RM Length L Ch R = 1 ,14752.94,96.404000,96.404000,96.404000
XS GIS Cut Line= 6
803703.331645295731005.202048431803684.115289404730926.788657902
803678.903095742730888.878554083803675.784346583730845.165359821
803674.259131278730699.858999153803669.977952533730626.670428589
#Sta/Elev= 30
9764.318432.76699785.421 421.1929795.831413.8495  9826.5396.99699836.724390.6392
9846.924384.81059857.018380.82899867.112374.55979877.206373.47179887.273373.4467
9897.299369.64439907.324366.91859927.375364.11549937.376363.92339947.377364.2605
9957.378361.66689967.379355.453610007.38355.189710027.38357.078810037.38   357.3
10047.38358.716710057.38363.029110067.38368.931610077.39381.9443 10087.4398.4915
10107.42398.836610117.43409.209810127.44425.195210137.49438.784710145.86450.8231
#Mann= 3 , 0 , 0
9764.318    0.04       09764.318    0.04       010145.86    0.04       0
#XS Ineff= 2 , 0
       0                               0
Bank Sta=9764.318,10145.86
Exp/Cntr=0.3,0.1

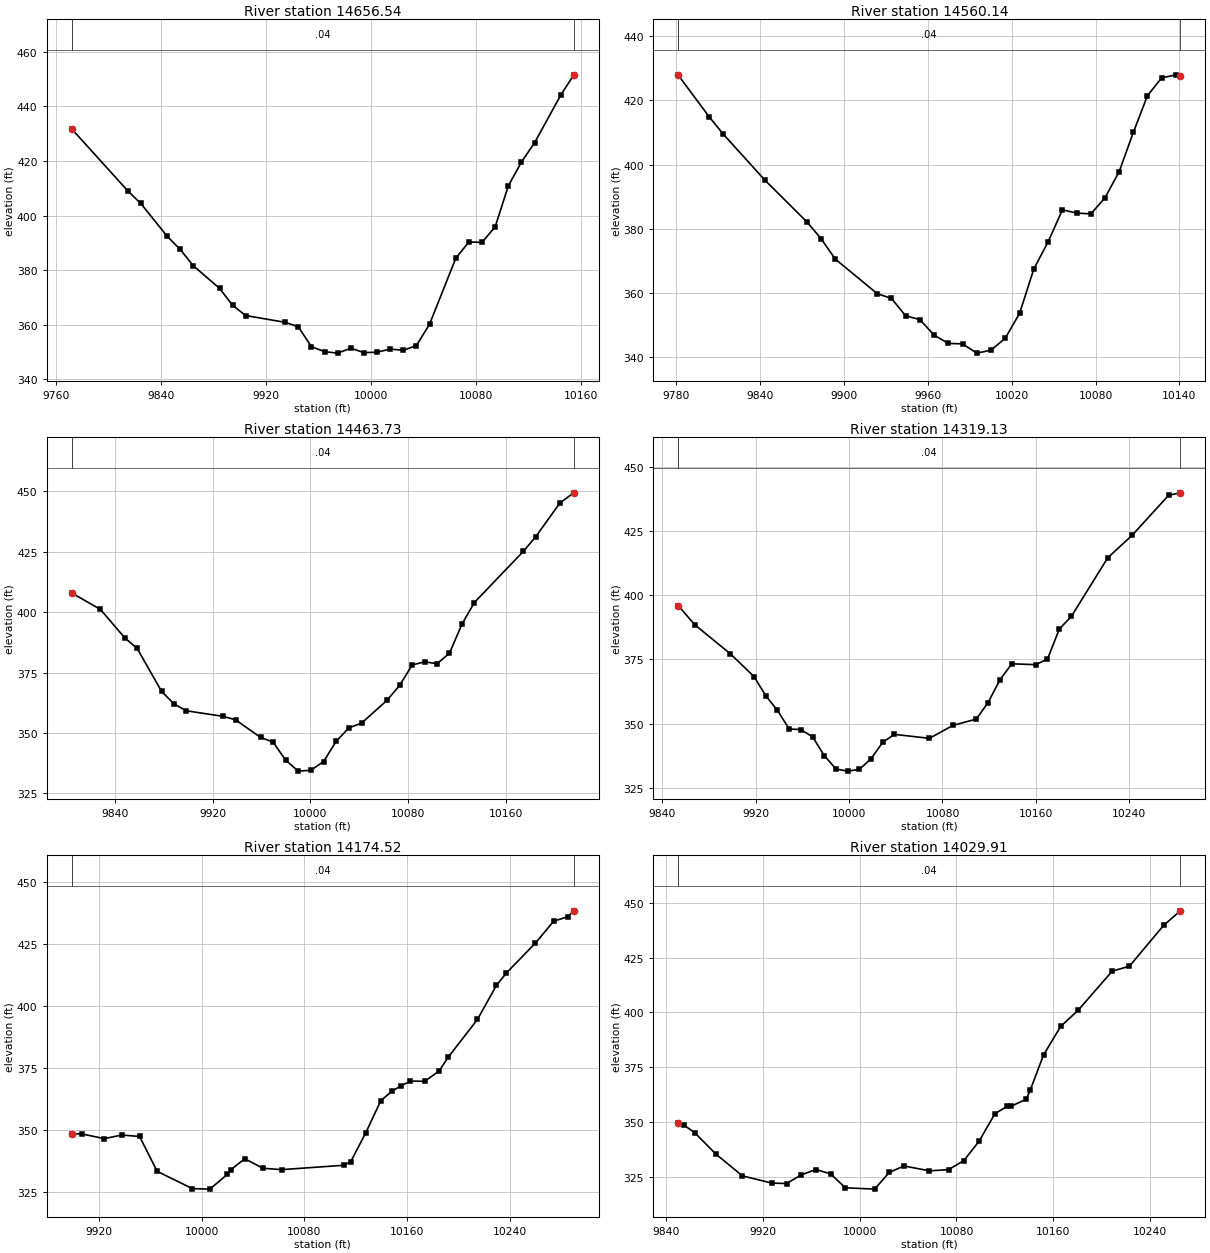
Type RM Length L Ch R = 1 ,14656.54,96.404000,96.404000,96.404000
XS GIS Cut Line= 6
  803780.0642608730997.101506665803774.294501248730956.695848579
803770.564877471 730875.70749226803771.136962163730770.597103878
803771.079191614730768.597938411 803772.78112939730615.063618292
#Sta/Elev= 30
9771.998431.75699814.512409.13069824.522404.47639844.543392.48569854.554387.6212
9864.565381.63449884.586373.32379894.596367.08159904.596363.34939934.596360.8809
9944.596 359.2389954.596351.96269964.597  350.129974.597349.58629984.597351.3802
9994.597 349.768 10004.6349.9318 10014.6351.0688 10024.6350.6245 10034.6352.3793
 10044.6360.1736 10064.6384.3947 10074.6390.3278 10084.6390.1851 10094.6395.8918
 10104.6410.8861 10114.6419.601610124.61426.695310144.61444.190910154.54451.5904
#Mann= 3 , 0 , 0
9771.998    0.04       09771.998    0.04       010154.54    0.04       0
#XS Ineff= 2 , 0
       0                               0
Bank Sta=9771.998,10154.54
Exp/Cntr=0.3,0.1

Type RM Length L Ch R = 1 ,14560.14,96.404000,96.404000,96.404000
XS GIS Cut Line= 6
803849.702113939730997.101506665803847.055063003730947.358724603
803848.771474492730895.110863042 803854.31421404730845.203673684
803881.671985014730708.884119412 803891.86703964730641.772695906
#Sta/Elev= 30
9781.443427.88779803.576414.9247 9813.59409.54149843.622395.08939873.638382.1016
9883.644376.92669893.705370.6091 9923.89359.76189933.954358.32359944.132352.8982
 9954.31351.71379964.488346.87349974.667344.28179984.845344.14039995.023341.2511
10005.23342.170210015.45345.914810025.67353.638410035.89367.5181 10046.1375.9564
10056.32385.922810066.54384.901310076.72384.655110086.83389.712110096.95397.8611
10107.06410.057710117.18421.530410127.29427.031910137.41428.001110140.67427.7049
#Mann= 3 , 0 , 0
9781.443    0.04       09781.443    0.04       010140.67    0.04       0
#XS Ineff= 2 , 0
       0                               0
Bank Sta=9781.443,10140.67
Exp/Cntr=0.3,0.1

Type RM Length L Ch R = 1 ,14463.73,144.606000,144.606000,144.606000
XS GIS Cut Line= 6
803937.341630995730998.451681793803937.907842964730917.604930967
803944.349956334730869.656734049803980.738892168730728.363858536
803991.795595288730668.470047861803994.826060037730593.768303673
#Sta/Elev= 30
9804.739407.92549828.212401.11579848.227389.29949858.234385.00679878.248367.1971
9888.276362.08559898.366359.17979928.636356.87349938.796355.43899959.277348.1456
9969.518346.2305  9979.8338.74049990.159334.195810000.52334.558910010.89338.1792
10021.26346.611810031.62352.101510041.99354.081310062.72363.468410073.09 369.658
10083.39378.117610093.56379.437310103.73378.651910113.89 382.97510124.06394.9476
10134.23403.950310174.44425.177110184.47431.172910204.48445.281210215.72449.3771
#Mann= 3 , 0 , 0
9804.739    0.04       09804.739    0.04       010215.72    0.04       0
#XS Ineff= 2 , 0
       0                               0
Bank Sta=9804.739,10215.72
Exp/Cntr=0.3,0.1

Type RM Length L Ch R = 1 ,14319.13,144.606000,144.606000,144.606000
XS GIS Cut Line= 6
804117.406542446 730978.72234461 804102.42780362730886.093266955
804101.631051234730767.551004242804097.720513831730717.364901301
804084.690127472730648.020032963804057.008808947 730555.67217298
#Sta/Elev= 30
 9853.77396.02239867.772388.60539898.386377.21519918.589368.35549928.655 360.898
9938.722355.12659948.782347.91659958.789347.66239968.797344.84179978.805 337.527
9988.808332.30469998.808331.475210008.81332.149210018.81336.277510028.81342.6867
10038.81345.804810068.82344.256810088.88349.291710108.94351.7753   10119358.2063
10129.18367.059410139.35373.3091 10159.7372.987410169.88375.126610180.05386.8883
 10190.3391.764610221.54 414.68810242.36423.4111 10273.6439.0079 10283.6439.9662
#Mann= 3 , 0 , 0
 9853.77    0.04       0 9853.77    0.04       0 10283.6    0.04       0
#XS Ineff= 2 , 0
       0                               0
Bank Sta=9853.77,10283.6
Exp/Cntr=0.3,0.1

Type RM Length L Ch R = 1 ,14174.52,144.606000,144.606000,144.606000
XS GIS Cut Line= 6
 804302.63683103730850.500658559804201.853528497730754.900260184
804177.834019475730729.525270236804151.403144349 730694.59126346
804131.488113647730661.918719635804071.783044427730540.897937497
#Sta/Elev= 30
9898.901348.54839906.602348.56139924.099346.64249937.964348.08259951.682347.5067
9965.401333.44969992.838 326.48810006.47326.287410020.02332.260710022.88334.1609
10033.57338.531610047.81 334.68610062.36334.142210110.62335.903510116.07337.3384
10127.82349.010310139.53 361.968 10148.1365.718910154.85367.808810162.56369.8185
10173.72369.759410184.87373.894210192.12379.557210214.72394.663210229.47408.3646
10237.32413.426910259.92425.491410274.07434.243810285.22436.1444 10289.8438.4599
#Mann= 3 , 0 , 0
9898.901    0.04       09898.901    0.04       0 10289.8    0.04       0
#XS Ineff= 2 , 0
       0                10033.55       0
Bank Sta=9898.901,10289.8
Exp/Cntr=0.3,0.1

Type RM Length L Ch R = 1 ,14029.91,144.606000,144.606000,144.606000
XS GIS Cut Line= 6
804428.750325938 730742.65363973804306.011570022730658.213619092
804255.469256161730623.471214769804226.588429881730601.610891101
804192.844210855730572.844610341804105.352717603730484.789290982
#Sta/Elev= 30
 9850.02349.45069854.573348.64949863.524345.24019881.167335.38279903.124325.4679
  9927.4322.16639939.538321.98769951.676 325.9219963.814328.34559975.952326.4118
 9988.09320.045310012.35319.424210024.49327.061110036.62329.981610057.63327.7726
10073.46328.3083   10086332.383510098.64341.223810111.78353.822910122.16 357.273
10124.92   357.210137.57360.368410140.89364.440710152.02380.674110166.21393.6741
 10180.4 400.89410208.77418.853410222.96421.083510251.34439.762310265.03446.3473
#Mann= 3 , 0 , 0
 9850.02    0.04       0 9850.02    0.04       010265.03    0.04       0
#XS Ineff= 2 , 0
       0 9902.69        10039.49       0
Bank Sta=9850.02,10265.03
Exp/Cntr=0.3,0.1

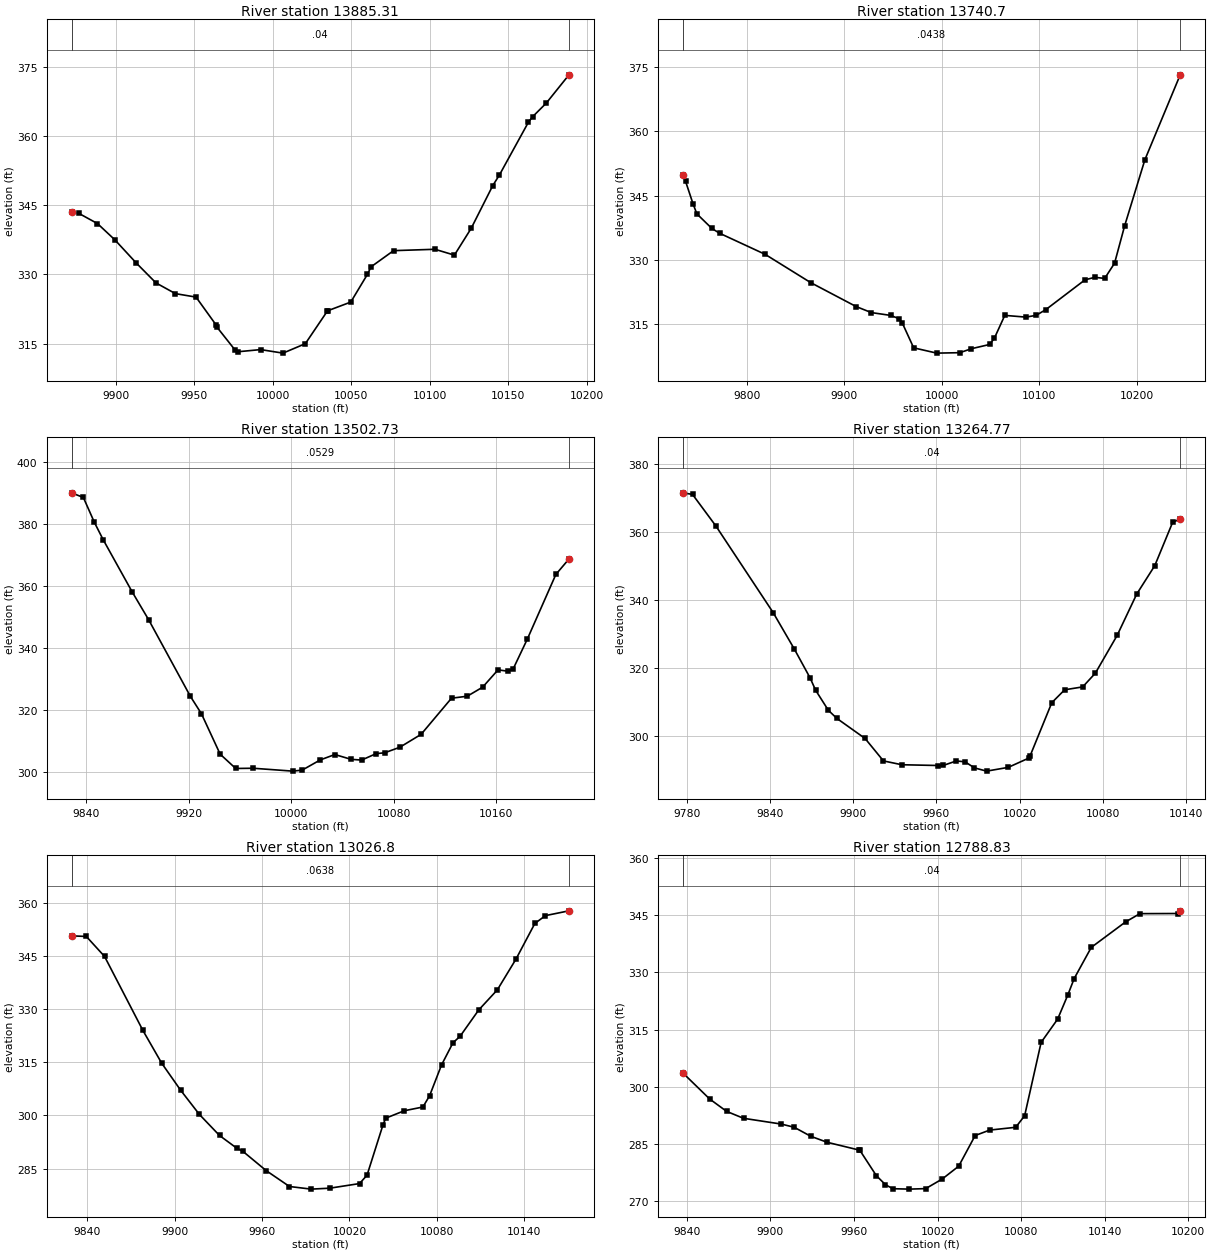
Type RM Length L Ch R = 1 ,13885.31,144.606000,144.606000,144.606000
XS GIS Cut Line= 6
804498.908592477730630.451704445804441.928058293730589.809832774
 804357.65997857730506.524402612804322.932659822730476.722340464
804294.477243213 730456.72010102804252.185318921730434.174228522
#Sta/Elev= 30
9871.763343.62779876.365343.24489888.297341.02089899.302337.52789913.134332.4443
9925.552 328.1849937.971325.85449951.111325.10569963.912319.0584 9964.57318.5461
9976.127313.58329978.129313.28329992.288313.736810006.52312.973410020.77 315.016
10034.66322.003210035.34 322.18310049.74  324.0310060.32 330.01710062.66331.6599
   10077335.160810103.36335.458610115.78334.192610126.47339.987810140.23349.2442
10144.49351.555610162.99362.993210165.56364.137210174.35 367.11210188.81  373.23
#Mann= 3 , 0 , 0
9871.763    0.04       09871.763    0.04       010188.81    0.04       0
#XS Ineff= 2 , 0
       0                               0
Bank Sta=9871.763,10188.81
Exp/Cntr=0.3,0.1

Type RM Length L Ch R = 1 , 13740.7,237.968200,237.968200,237.968200
XS GIS Cut Line= 6
804707.414243838730570.493605217804436.670123935730403.377897039
804398.475679517730387.752897039804361.149290621730387.752897039
804313.406235069730395.565397039804250.198455639730413.967661963
#Sta/Elev= 30
9733.864349.71519736.686348.37989744.475343.04599748.374340.74039763.791337.3367
9771.751336.21969818.505331.30329865.258324.71229912.012319.12089927.551317.7222
9947.352317.06519955.897316.30539959.205315.37919971.058309.49919994.764308.2641
10018.47308.367610030.32309.291410049.03310.279710053.85311.691110064.66 317.068
10086.27316.664410096.79317.068510106.79318.404510147.01325.350510157.14325.9481
10167.27325.690310177.41329.229610187.78 337.96510208.61353.389610244.85373.1725
#Mann= 3 , 0 , 0
9733.864  0.0438       09733.864  0.0438       010244.85  0.0438       0
#XS Ineff= 2 , 0
       09950.379                       0
Bank Sta=9733.864,10244.85
Exp/Cntr=0.3,0.1

Type RM Length L Ch R = 1 ,13502.73,237.968200,237.968200,237.968200
XS GIS Cut Line= 6
804532.571302801 730100.50081715804460.910982609730159.208069623
804346.662582397730291.931359291 804322.58881548730312.431712419
804287.571575314730335.745585203804245.339165786730354.909277159
#Sta/Elev= 30
9828.463390.12129837.702388.61359846.297380.56359853.099375.00329875.834  358.05
9888.702349.03349921.195324.31619929.831318.68659944.441305.61189956.571300.9868
9970.209301.0601   10001 300.12910008.41300.446710022.56303.754110033.91305.4945
10046.65 303.93910054.81303.705210066.24305.796310072.75306.049310084.64307.8485
10101.25312.022510124.97323.708810137.26324.350410149.27327.278710161.28332.8724
10168.86 332.44910173.07333.1589 10184.2342.871710206.43363.747310216.65368.7275
#Mann= 3 , 0 , 0
9828.463  0.0529       09828.463  0.0529       010216.65  0.0529       0
#XS Ineff= 2 , 0
       0                               0
Bank Sta=9828.463,10216.65
Exp/Cntr=0.3,0.1

Type RM Length L Ch R = 1 ,13264.77,237.968300,237.968300,237.968300
XS GIS Cut Line= 6
804359.815867007729917.608078137804312.814297259729967.528432012
804250.868040174730039.055025533804213.144442171730083.922041535
804211.830535918730085.429904401804126.021636024730189.128626375
#Sta/Elev= 30
9777.194371.60299784.219371.14089801.082361.81069842.286336.29249857.695325.4309
9868.872317.0518 9872.97313.33339882.101 307.4439888.245305.04769908.559 299.129
9921.788292.51049935.017291.38199961.214291.15649965.039291.19799974.278292.4985
9980.578292.24839987.343290.45799996.117289.497910011.71290.6073 10026.4293.3221
 10027.4293.944410043.09309.691210052.36313.496110065.34314.344410074.46318.3934
10090.14329.515610104.28341.741410117.26350.103510130.24362.9917 10135.6363.7776
#Mann= 3 , 0 , 0
9777.194    0.04       09777.194    0.04       0 10135.6    0.04       0
#XS Ineff= 2 , 0
       0                               0
Bank Sta=9777.194,10135.6
Exp/Cntr=0.3,0.1

Type RM Length L Ch R = 1 , 13026.8,237.968200,237.968200,237.968200
XS GIS Cut Line= 6
804139.416626841729797.161413163804085.241447151729862.963677257
804032.409521967729929.107096061804031.164461434729930.672287479
803943.969047368730040.084463716803924.454663706730062.749161715
#Sta/Elev= 30
9829.112350.69439839.266350.51869851.794344.87689878.125323.99239891.078314.7213
9904.031307.12689916.953300.27149930.757294.3372 9942.55290.7648 9946.78289.8727
9962.803284.42269978.826279.93199993.744279.193310006.53279.460410026.94 280.761
10032.11283.140310042.98297.2333 10044.9299.213410057.68301.320210070.47302.3733
10075.07305.553610083.26314.236910091.12320.495510096.04322.350810108.83329.7756
10121.62335.457310134.41 344.12310147.39354.196110154.65356.403310170.82357.7542
#Mann= 3 , 0 , 0
9829.112  0.0638       09829.112  0.0638       010170.82  0.0638       0
#XS Ineff= 2 , 0
       0                               0
Bank Sta=9829.112,10170.82
Exp/Cntr=0.3,0.1

Type RM Length L Ch R = 1 ,12788.83,237.968200,237.968200,237.968200
XS GIS Cut Line= 6
803925.095606595  729659.0259839803878.044499844729727.591701716
803835.244424731 729796.16061236803773.294728607729893.776471347
803742.129645586729937.456129491803727.172440345729956.197711465
#Sta/Elev= 30
9837.013303.62719856.386296.74539868.514293.50899880.642 291.6949907.877290.1721
9917.026289.34049928.903 286.9789940.692285.39699963.684283.3539 9964.27283.2452
9976.059276.62469982.567274.26939987.847273.20939999.635 273.09810011.47273.2316
10023.31275.743310035.16279.1137   10047 287.16910057.44288.598910076.11289.3292
10082.53292.369310094.38  311.6310106.22317.722310113.43323.971210118.12328.3872
 10130.4336.566210154.97343.237810165.33345.421510192.72345.454110194.25346.1601
#Mann= 3 , 0 , 0
9837.013    0.04       09837.013    0.04       010194.25    0.04       0
#XS Ineff= 2 , 0
       0                               0
Bank Sta=9837.013,10194.25
Exp/Cntr=0.3,0.1