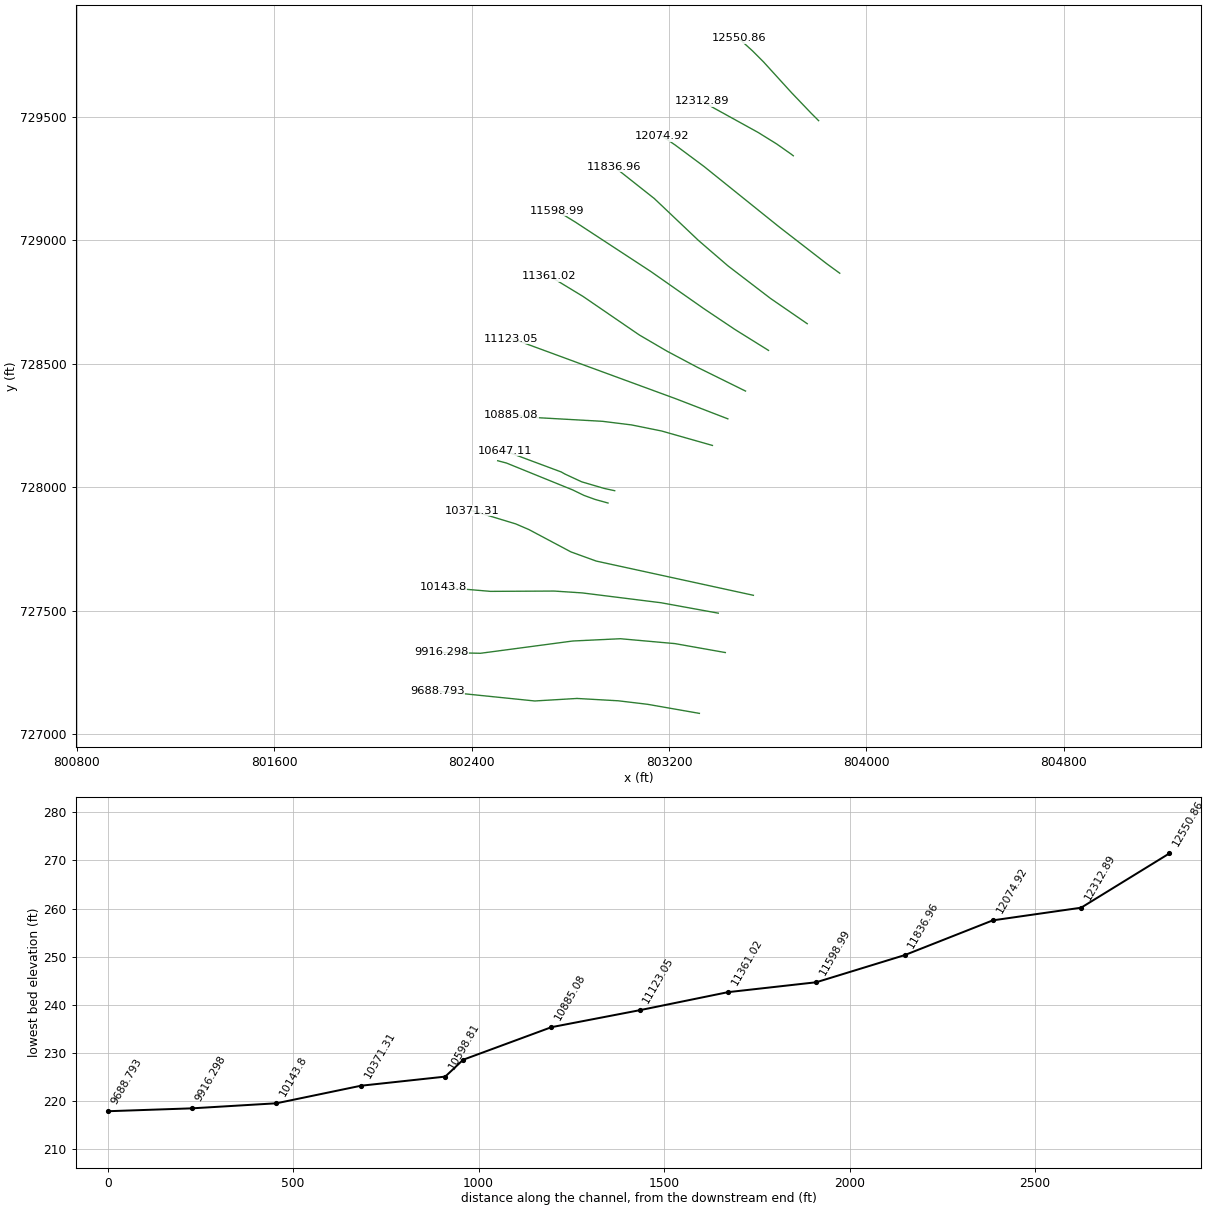
HEC-RAS study 6817_ras.prj: 6817

--- 6817_ras.g01 (geometry) --- (continued)

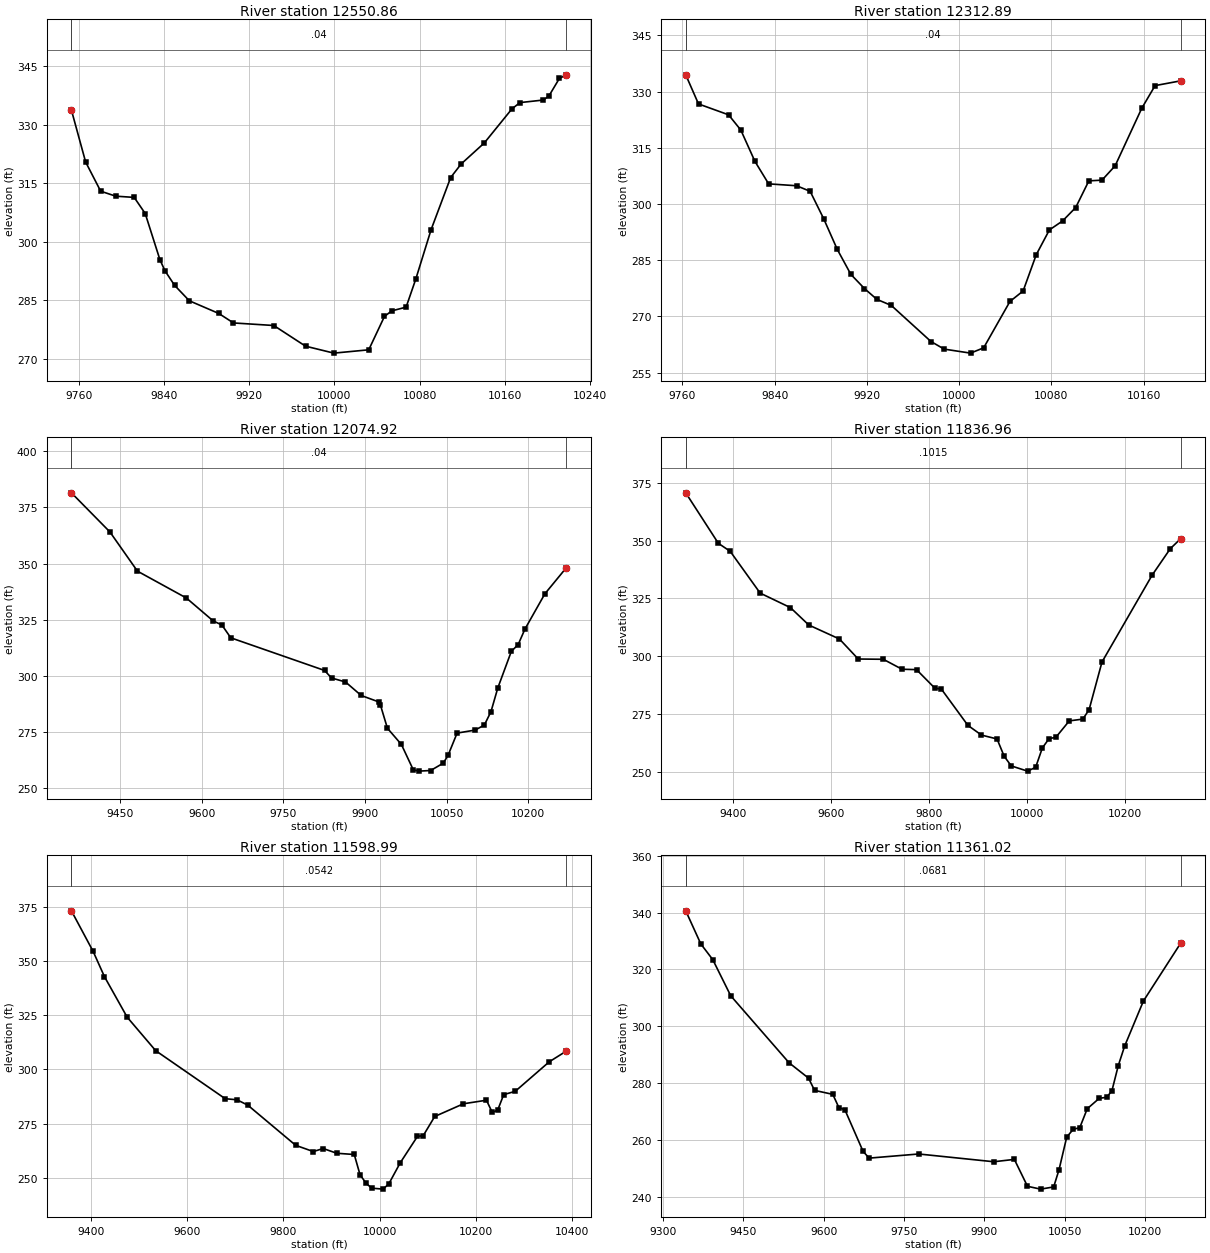
Type RM Length L Ch R = 1 ,12550.86,237.968200,237.968200,237.968200
XS GIS Cut Line= 6
803806.518884808729485.558767959 803775.09996894729516.943054616
803695.654748231 729600.09367533 803582.71042493729724.242517158
803539.676295459729767.376636162 803482.56110933729819.240587076
#Sta/Elev= 30
9752.719333.79799766.078320.48539780.228312.99939794.378311.71879811.748 311.405
9822.102307.27339835.932295.42529840.699292.57479849.763288.83939863.593 284.891
9891.255281.64439905.085279.21019942.989278.5529 9972.87273.24919999.492271.4688
10032.27272.318610047.04280.873910053.83282.298410067.41283.264810076.59290.5306
10090.89303.125810109.29316.4986 10119.2319.9921 10140.9325.362110166.92334.1094
10174.44335.716210196.45336.374710201.62 337.38810211.49341.908410218.06342.8379
#Mann= 3 , 0 , 0
9752.719    0.04       09752.719    0.04       010218.06    0.04       0
#XS Ineff= 2 , 0
       09936.456                       0
Bank Sta=9752.719,10218.06
Exp/Cntr=0.3,0.1

Type RM Length L Ch R = 1 ,12312.89,237.968300,237.968300,237.968300
XS GIS Cut Line= 6
803703.811123908729343.261190653803693.809799582729350.880501956
803636.717151314729391.001100883803561.541605443729437.671924025
803380.163045824729537.779752657803335.834984026729563.649022695
#Sta/Elev= 30
9762.896334.45789773.972326.68679800.026323.78979810.681319.71879822.903311.3628
9834.811305.3548 9859.04304.8489 9870.81303.36719882.581296.03369894.351287.8561
9906.122281.19719917.892277.42079928.667274.52979941.229272.89869975.605263.2756
9987.064261.244410009.93260.172110021.33261.583210044.15273.969610055.55 276.755
10066.96286.448210078.36293.062810089.77295.448310101.17299.035510112.58306.1534
10123.98306.345510135.39310.178410158.46325.519410170.04331.579110192.23332.8522
#Mann= 3 , 0 , 0
9762.896    0.04       09762.896    0.04       010192.23    0.04       0
#XS Ineff= 2 , 0
       0                               0
Bank Sta=9762.896,10192.23
Exp/Cntr=0.3,0.1

Type RM Length L Ch R = 1 ,12074.92,237.968200,237.968200,237.968200
XS GIS Cut Line= 6
803892.094003886728867.240467459803840.307520688728904.915024891
803645.806987345729055.546285614803342.111480117729299.824675024
803225.374565154729386.661267862803172.478737258 729422.90858971
#Sta/Elev= 30
9360.537381.53139431.291364.10199481.884346.63429571.703334.68159621.014324.4642
9637.031322.64919653.363316.93719825.647302.39769838.482299.03869864.153297.2611
9893.036291.23549924.939288.40969928.329287.00459941.165276.64769966.835269.4313
9988.745258.1006    9999257.540210020.68257.816110043.81261.097210052.63264.5895
 10069.2274.485910102.51275.838210119.27278.072610131.51284.075210143.98294.5756
 10168.9310.921510181.37 313.89510193.83320.799310230.53336.551210269.95348.1741
#Mann= 3 , 0 , 0
9360.537    0.04       09360.537    0.04       010269.95    0.04       0
#XS Ineff= 2 , 0
       0                               0
Bank Sta=9360.537,10269.95
Exp/Cntr=0.3,0.1

Type RM Length L Ch R = 1 ,11836.96,237.968200,237.968200,237.968200
XS GIS Cut Line= 6
 803760.26641795728662.719348967803611.334683061728765.199778274
803438.725859731728897.335559353803319.669368088728999.981269568
803140.471821755729169.975953713802977.934149765729298.485166974
#Sta/Elev= 30
 9303.69370.68559370.186348.85689394.417345.37449455.551 327.3039517.325321.0242
9554.734313.50449617.316307.44549655.599298.79499706.747298.68249745.005294.3696
9774.495294.20289811.928286.1821 9825.28285.77079879.372270.08759907.011265.8959
9938.816264.21019953.305256.74499967.793252.5587   10001250.298910017.52251.9312
10031.25260.341810044.98264.3733 10058.7264.906410086.16272.028410113.81272.8055
10126.52276.8267 10152.9297.507510255.31335.113410292.35346.550510313.42350.8347
#Mann= 3 , 0 , 0
 9303.69  0.1015       0 9303.69  0.1015       010313.42  0.1015       0
#XS Ineff= 2 , 0
       0                               0
Bank Sta=9303.69,10313.42
Exp/Cntr=0.3,0.1

Type RM Length L Ch R = 1 ,11598.99,237.968200,237.968200,237.968200
XS GIS Cut Line= 6
803603.445299745728554.446645439803468.596158415 728638.42527999
803343.169117272728722.389020339803126.434081882728874.216148019
802819.624948114729075.060918584802744.630916774729120.992707919
#Sta/Elev= 30
9359.309373.33799404.493 354.5679428.077342.87319475.246 324.1629534.535308.6785
9679.084286.46969703.503285.97359725.948283.50189825.598264.91839862.227262.0354
9882.812263.43729911.065261.24369947.402260.67499959.357251.35759971.311247.5841
9983.266245.121410007.16244.661710019.11247.045810043.02256.838910078.87269.0706
10090.82269.390410114.73278.249110174.49284.1314 10222.3285.770610234.25280.1542
10245.55281.161710258.15288.350710282.07289.881710352.77303.524610388.38308.4938
#Mann= 3 , 0 , 0
9359.309  0.0542       09359.309  0.0542       010388.38  0.0542       0
#XS Ineff= 2 , 0
       0                               0
Bank Sta=9359.309,10388.38
Exp/Cntr=0.3,0.1

Type RM Length L Ch R = 1 ,11361.02,237.968300,237.968300,237.968300
XS GIS Cut Line= 6
803510.249756336728389.624596775803315.515103579 728485.74118343
803192.596237391728551.027924716803079.850714207728616.949538991
802852.109225065728772.919175223802715.026039016728856.158672289
#Sta/Elev= 30
9342.772340.6033 9370.93328.94239393.234 323.4099426.689310.69979535.668287.0713
9571.842281.69539583.165277.36749617.134 275.9829628.457271.3413 9639.78270.5176
9673.749255.85769685.072253.5215 9777.42 254.9779917.549252.24299955.887253.0752
  9980.4243.5961 10004.9242.602410029.24243.376610039.26249.452510053.58260.9277
10065.75263.673210077.92264.238910091.89270.912610114.21274.568110128.26274.9572
10137.93277.246910149.79286.100210161.65292.9695 10196.7308.852610266.19329.2056
#Mann= 3 , 0 , 0
9342.772  0.0681       09342.772  0.0681       010266.19  0.0681       0
#XS Ineff= 2 , 0
       09930.777                       0
Bank Sta=9342.772,10266.19
Exp/Cntr=0.3,0.1

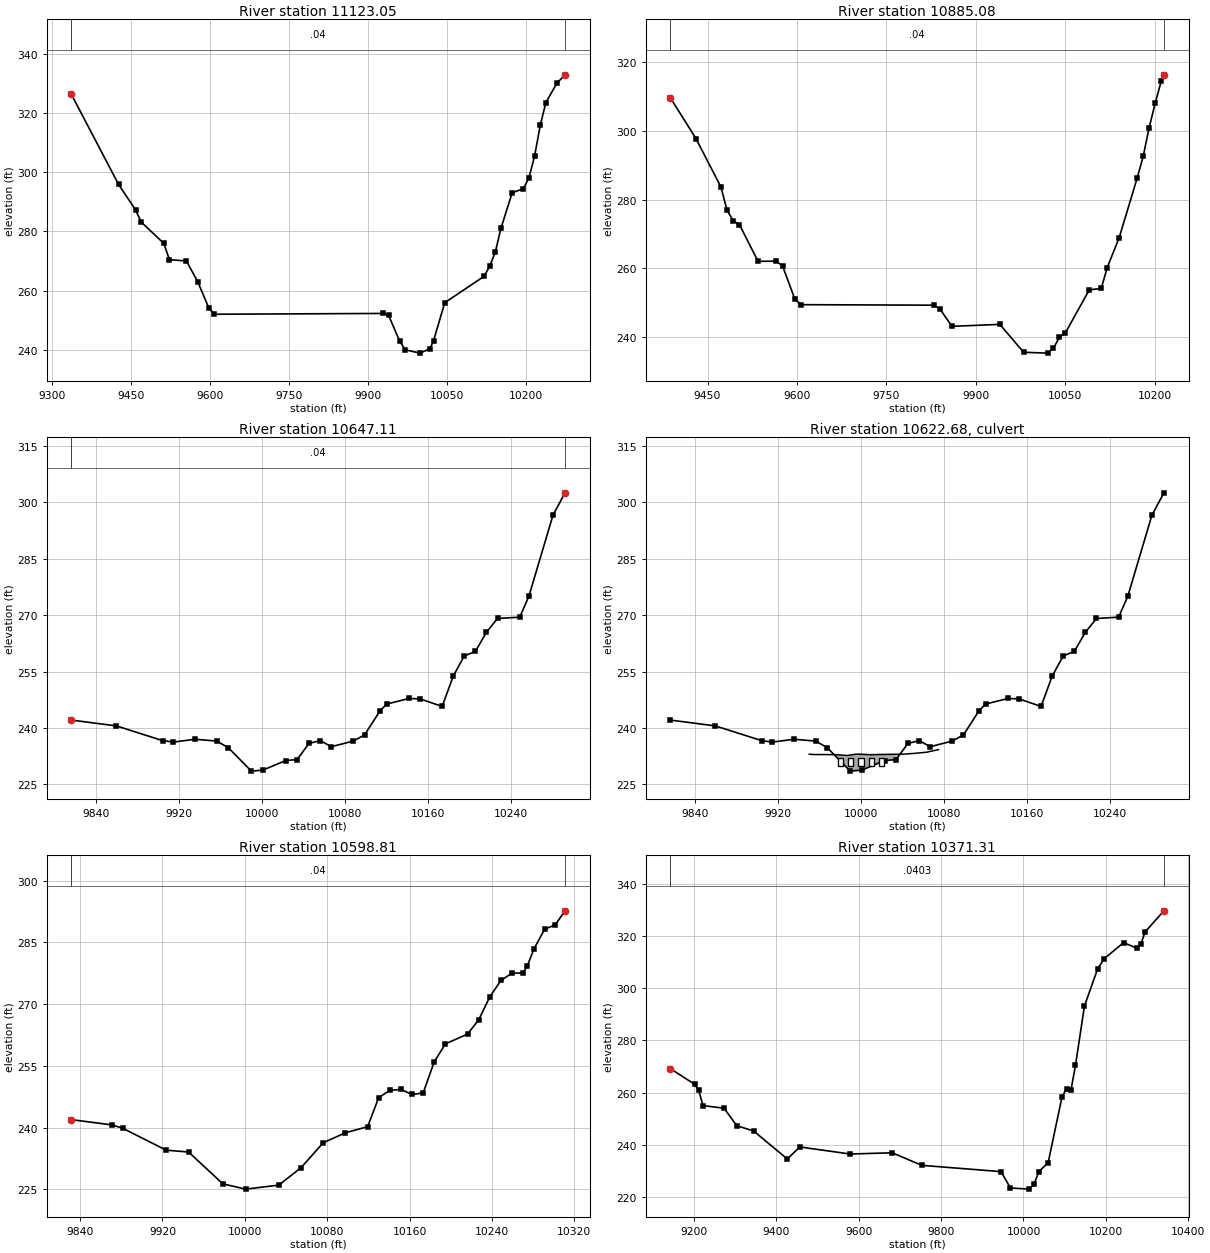
Type RM Length L Ch R = 1 ,11123.05,237.968200,237.968200,237.968200
XS GIS Cut Line= 6
803438.550004691728277.065428913803228.043088615728358.342195049
802818.810392201728508.506302699802816.962112457728509.270411283
802611.611704946 728584.77917859802560.714650832728602.642387351
#Sta/Elev= 30
9337.434326.32219426.995295.86129459.154287.28999469.873283.15819512.751275.9415
9523.471270.43289555.629269.9916 9576.98263.04619598.284254.06149608.936251.9893
9928.495252.25959939.147251.62399960.451242.79059971.103239.9504    9999238.8483
 10017.6240.3585 10024.4243.047510045.71 255.90310120.29264.807910130.95268.2254
 10141.6273.003910152.26281.025110173.56293.045510194.87294.426110205.53298.1648
10216.18305.5434 10226.8315.7779 10237.4323.524610258.59 330.12110273.73332.9011
#Mann= 3 , 0 , 0
9337.434    0.04       09337.434    0.04       010273.73    0.04       0
#XS Ineff= 2 , 0
       09896.261                       0
Bank Sta=9337.434,10273.73
Exp/Cntr=0.3,0.1

Type RM Length L Ch R = 1 ,10885.08,237.968200,237.968200,237.968200
XS GIS Cut Line= 6
803376.134271622728169.265241757803170.274814993728227.764079198
803047.894004971728252.496274441 802930.08122161728267.090321273
802670.521621495728281.622483626802560.445106329 728292.81384083
#Sta/Elev= 30
9387.437309.73439430.641 297.7859472.306283.76139482.722276.93099493.138273.8819
9503.554272.73689534.685262.05979565.654262.10469575.978260.65719596.624250.9597
9606.902249.43059830.117249.28189840.168248.09519860.216243.11849940.341243.6961
9980.403235.561810020.46235.315710030.48236.7667 10040.5239.955110050.51241.2453
10090.58253.766410110.62254.158410120.66260.252310140.73268.970710170.86286.3126
10180.93292.5988   10191301.037610201.08308.081410211.15314.485110215.74316.3852
#Mann= 3 , 0 , 0
9387.437    0.04       09387.437    0.04       010215.74    0.04       0
#XS Ineff= 2 , 0
       09927.506                       0
Bank Sta=9387.437,10215.74
Exp/Cntr=0.3,0.1

Type RM Length L Ch R = 1 ,10647.11,48.303500,48.303500,48.303500
XS GIS Cut Line= 6
802980.062051028727985.767219976802938.482189953727994.766062573
802846.121078789728021.849395901802777.718301058728053.620229229
 802763.51828903728061.679695532802534.163689166728147.136337265
#Sta/Elev= 30
9816.288242.11799859.662 240.5689904.144236.65989914.565236.26799935.407237.0123
9956.326 236.5349967.431234.77139989.642228.539710000.75228.814410022.68231.3537
10033.66231.603710045.16235.909810055.95236.660510066.62235.034310087.96 236.551
10098.64238.181910113.65244.618210119.98246.380210141.32247.856510151.99247.7678
10173.34245.743910184.01253.793110194.68259.176610205.35260.376910216.02265.4767
10226.69269.139710248.04269.489110256.86275.049610280.05296.596610291.62302.5584
#Mann= 3 , 0 , 0
9816.288    0.04       09816.288    0.04       010291.62    0.04       0
#XS Ineff= 2 , 0
       0  9878.2                       0
Bank Sta=9816.288,10291.62
Exp/Cntr=0.3,0.1

Type RM Length L Ch R = 2 ,10622.68,,,
Bridge Culvert--1,0,-1,-1, 0
Deck Dist Width WeirC Skew NumUp NumDn MinLoCord MaxHiCord MaxSubmerge Is_Ogee
13.152,22,2.6,0,19,19, , , 0.95, 0, 0,0,,
 9950.08 9953.96 9964.92 9969.53 9975.87 9986.82 9994.06 9997.7710008.7210018.58
10019.6710030.6310041.5810043.1110052.5310063.4810067.6310074.4310074.62
  233.04  232.96  232.94  232.94  232.92  232.70  233.02  233.06  232.91  232.97
  232.97  233.02  233.06  233.10  233.29  233.58  233.85  234.24  234.25
                                                                                
                                                                        
 9950.08 9953.96 9964.92 9969.53 9975.87 9986.82 9994.06 9997.7710008.7210018.58
10019.6710030.6310041.5810043.1110052.5310063.4810067.6310074.4310074.62
  233.04  232.96  232.94  232.94  232.92  232.70  233.02  233.06  232.91  232.97
  232.97  233.02  233.06  233.10  233.29  233.58  233.85  234.24  234.25
                                                                                
                                                                        
BR Coef=-1 , 0 , 0 ,, 0 ,,,0.8,-1,,0,
WSPro=,,,, 1 ,,,, 0 ,,,, 0 ,,,,-1 ,-1 ,-1 , 0 , 0 , 0 , 0 , 0
Multiple Barrel Culv=2,2,5,22,0.013,0.5,1,8,3,230,226,5,Culvert #1, 0, 13.152
 9980.00 9980.00 9990.00 9990.0010000.0010000.0010010.0010010.0010020.0010020.00
Culvert Bottom n=0.013
BC Design=,, 0 ,, 0 ,,,,,,

Type RM Length L Ch R = 1 ,10598.81,227.504500,227.504500,227.504500
XS GIS Cut Line= 6
802952.935314953727935.854025528 802901.18199718727950.238949299
802855.848831177727966.612089962802809.802630574727988.944270536
802541.232080132728097.974058196802505.851174563728107.295946211
#Sta/Elev= 30
9831.451241.92149870.809240.65439881.199239.85169923.636234.49669945.346234.0527
9978.594226.322310000.66225.030610032.92226.0029 10054.5230.217610076.09236.2928
10097.67238.732610119.26240.206510130.05247.298910140.84249.031110151.64249.2728
10162.43248.041510173.22248.422110184.01255.992110194.81260.336310216.39262.7405
10227.18 266.20810237.98271.774210248.77275.791710259.56277.544210270.35277.5875
10274.42279.329810280.87283.426110291.21288.215210301.55289.288510311.01   292.7
#Mann= 3 , 0 , 0
9831.451    0.04       09831.451    0.04       010311.01    0.04       0
#XS Ineff= 2 , 0
       0                               0
Bank Sta=9831.451,10311.01
Exp/Cntr=0.3,0.1

Type RM Length L Ch R = 1 ,10371.31,227.504500,227.504500,227.504500
XS GIS Cut Line= 6
803542.097911328727561.896435231802905.298095942727700.588621378
802802.701536328727737.744731352802632.299813837727828.303174257
802578.823757052727851.290965244802400.785026133727905.369965062
#Sta/Elev= 30
 9142.45269.22939201.345263.2616 9211.66260.87239221.901255.08559273.099254.0864
9303.817247.38669344.776245.37979426.514234.67599457.087239.25869579.379236.5632
9681.342237.03229753.295232.23279945.496229.82419968.284223.574710014.15223.1312
10025.64225.004510037.13229.806710059.88233.227810093.52258.3989 10104.5261.5931
10115.38261.037810126.27270.497210148.04293.1734   10180307.385310196.22311.3126
10243.26317.449510274.48315.332210284.89316.8242 10295.3321.530110340.95329.5935
#Mann= 3 , 0 , 0
 9142.45  0.0403       0 9142.45  0.0403       010340.95  0.0403       0
#XS Ineff= 2 , 0
       09871.315                       0
Bank Sta=9142.45,10340.95
Exp/Cntr=0.3,0.1

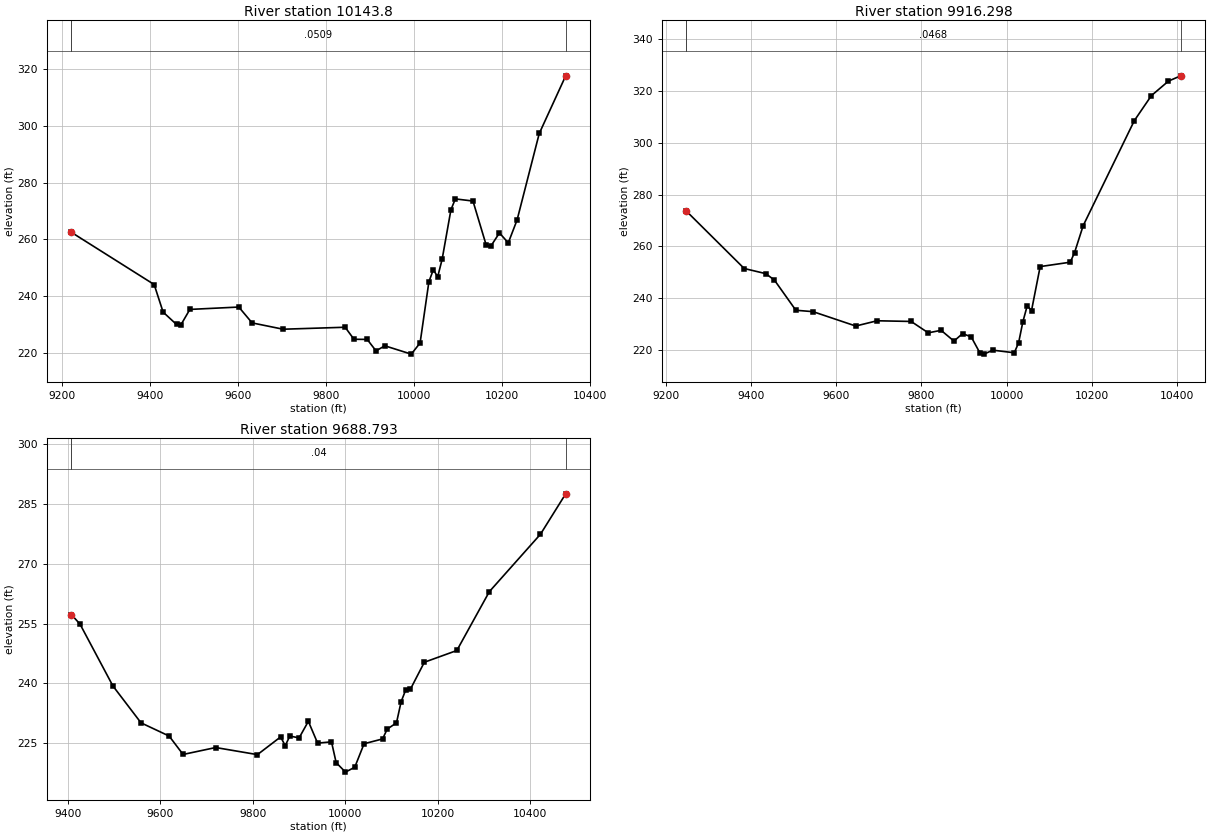
Type RM Length L Ch R = 1 , 10143.8,227.504600,227.504600,227.504600
XS GIS Cut Line= 6
803399.734349668727489.504819259803167.973458171727531.693388209
802848.275634825727571.591132089802734.768515021 727579.06535989
802476.839237809727577.809183687802285.289619029727594.137200162
#Sta/Elev= 30
9222.342262.46289410.234244.03579430.521234.31019460.938229.95099471.035229.8545
 9491.23235.26069602.297236.09529632.497230.50099702.937228.26999843.628228.9671
9863.653224.72789893.683224.67519913.688220.63119933.693222.41999993.709219.4819
10013.71 223.41310033.71 245.03710043.71249.240910053.71246.794310063.71252.9256
10083.71270.416810093.72274.255510133.72 273.50110163.75257.949310173.77257.4634
10193.81262.249510213.85258.741610233.89266.848510284.13297.337610344.17317.6856
#Mann= 3 , 0 , 0
9222.342  0.0509       09222.342  0.0509       010344.17  0.0509       0
#XS Ineff= 2 , 0
       09734.665                       0
Bank Sta=9222.342,10344.17
Exp/Cntr=0.3,0.1

Type RM Length L Ch R = 1 ,9916.298,227.504500,227.504500,227.504500
XS GIS Cut Line= 6
803428.363757074727329.854249254 803224.30648464727366.075021267
803002.925987005727385.882400453802809.465605527727376.601194203
802436.054638565 727326.89644894802276.371797383727330.247761756
#Sta/Elev= 30
9248.479273.63849384.173251.48829434.803 249.5039455.054247.02179505.386235.3664
9545.647234.83099645.981 229.2789696.034231.30919776.067231.04489816.136226.6473
9846.296227.62499876.481223.46239896.701226.35619916.922225.09129937.142218.9813
9947.252 218.4319967.472 219.96510018.05 218.95610028.17222.778510038.29230.9738
10048.42237.100310058.54 235.26310078.79252.226510149.49253.921610159.57257.6549
10179.69268.0079 10299.9 308.59810339.91318.241810379.98323.841510408.65325.8732
#Mann= 3 , 0 , 0
9248.479  0.0468       09248.479  0.0468       010408.65  0.0468       0
#XS Ineff= 2 , 0
       0                               0
Bank Sta=9248.479,10408.65
Exp/Cntr=0.3,0.1

Type RM Length L Ch R = 1 ,9688.793,227.504500,227.504500,227.504500
XS GIS Cut Line= 6
803323.196099639727083.334075466803113.085926205727120.133194998
802994.588411957727134.318233699802827.199571878727143.823056296
802655.880068779727133.603436872802260.982791305727173.960785553
#Sta/Elev= 30
  9407.7 257.2339426.238254.87869497.554239.3825 9558.33230.15799619.098226.8574
9649.323222.24669719.823 223.9819810.172222.20529860.263226.63199870.268224.4557
9880.272226.8578 9900.28 226.3899920.291230.53469940.304225.0858 9970.35225.3991
9980.423220.209910000.58217.827710020.72219.065710040.81224.929610080.82226.1314
10090.86228.584310110.94230.168410120.98 235.45810131.02  238.4310141.06238.5755
10171.18245.317510241.47248.256310311.78262.980110422.41277.348610476.94287.4492
#Mann= 3 , 0 , 0
  9407.7    0.04       0  9407.7    0.04       010476.94    0.04       0
#XS Ineff= 2 , 0
       09764.876                       0
Bank Sta=9407.7,10476.94
Exp/Cntr=0.3,0.1