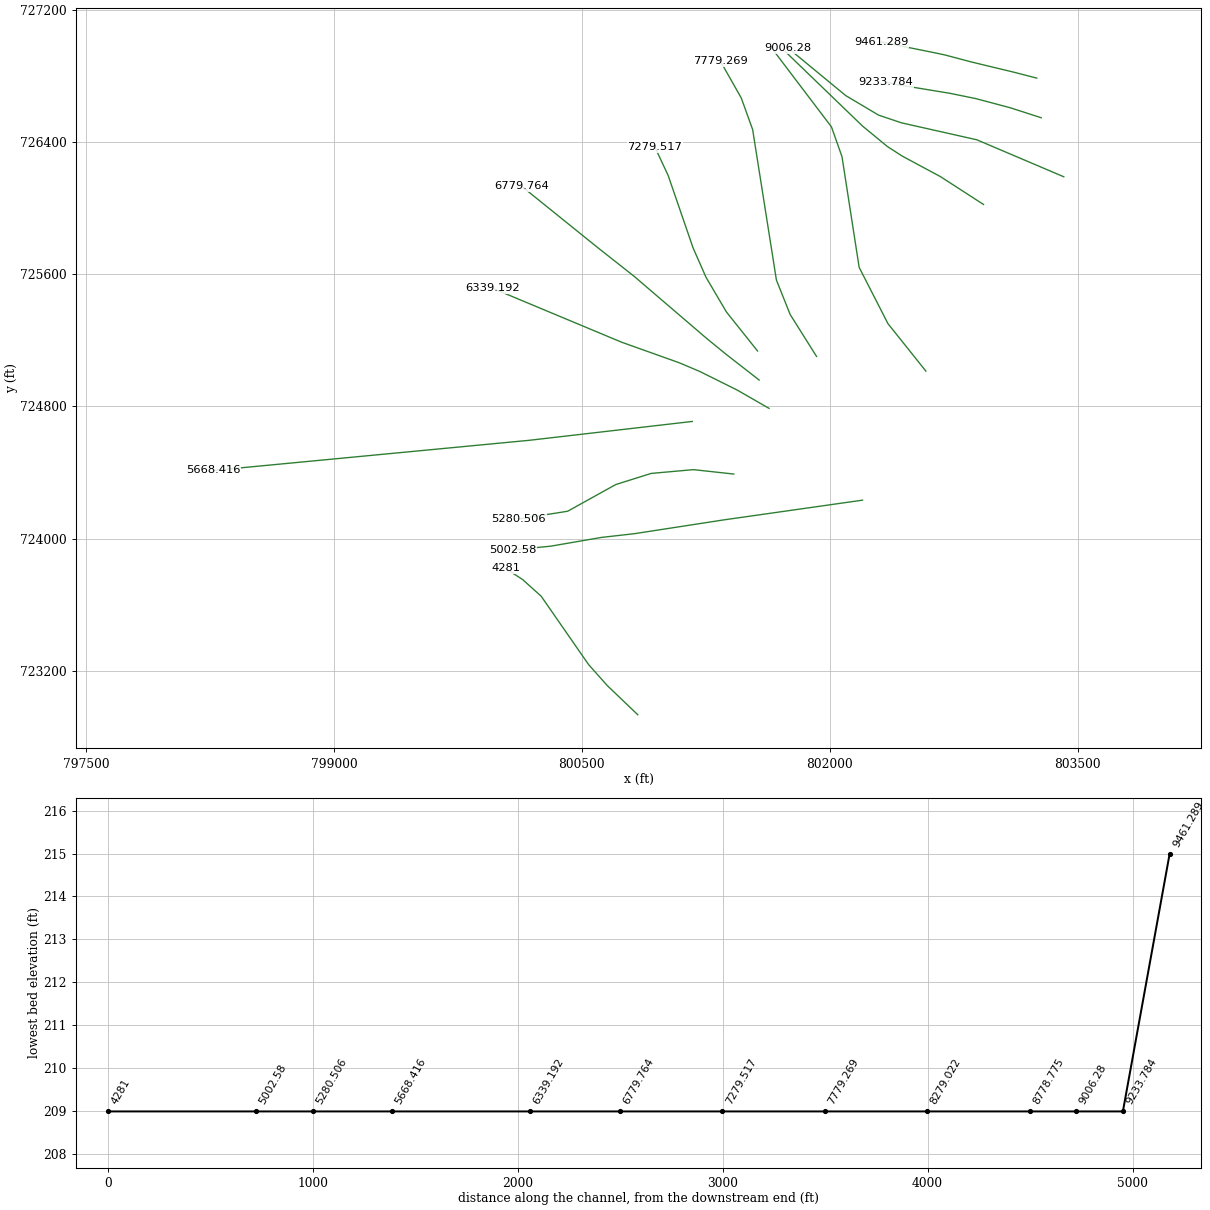
HEC-RAS study 6817_ras.prj: 6817

--- 6817_ras.g01 (geometry) --- (continued)

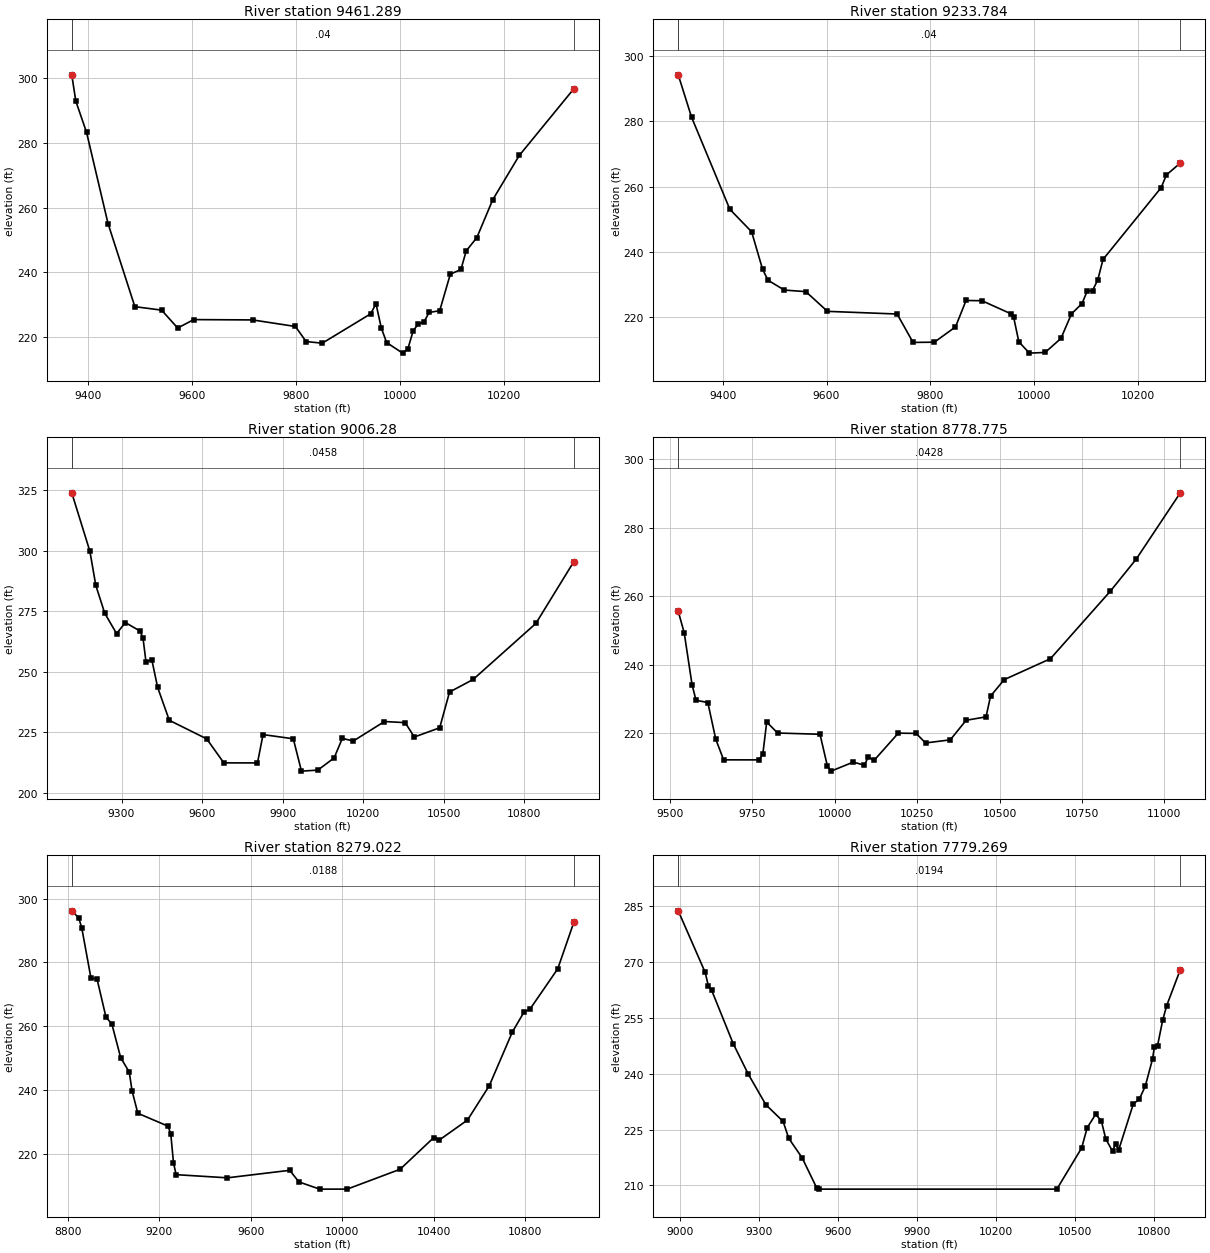
Type RM Length L Ch R = 1 ,9461.289,227.504500,227.504500,227.504500
XS GIS Cut Line= 6
803252.454598337726785.438153222803114.341009974726821.124951467
802853.200045258726884.023047939 802698.52867955 726925.08558175
802638.563753575726937.931087926802312.123556763727003.993515685
#Sta/Elev= 30
9368.383301.10329376.135292.96619396.801283.30459438.094255.0945 9489.71229.3587
9541.216228.28129572.074222.74469602.932225.35539716.078225.25629798.476 223.228
9819.169218.55739850.208218.05729943.284227.14559953.511230.26389963.738222.7514
9973.966218.262810004.64214.979710014.84 216.32210025.04221.883910035.24224.0963
10045.45224.521510055.65227.559610076.06228.110510096.46239.412410116.87240.8594
10127.07 246.62310147.47250.723110178.08262.4542 10229.1276.148710334.06296.7886
#Mann= 3 , 0 , 0
9368.383    0.04       09368.383    0.04       010334.06    0.04       0
#XS Ineff= 2 , 0
       09541.048                       0
Bank Sta=9368.383,10334.06
Exp/Cntr=0.3,0.1

Type RM Length L Ch R = 1 ,9233.784,227.504600,227.504600,227.504600
XS GIS Cut Line= 6
803279.297745705726545.637890041803092.351608425726605.930241823
802883.712136805726661.461801603802727.829378068726693.359269619
802412.292747408726745.320734531802338.972351859726761.541695318
#Sta/Elev= 30
9314.543294.29249340.227281.28899413.885253.07119455.807246.18319476.768234.7416
9487.248231.34159518.624228.32059560.186 227.8369601.749221.7928 9735.83220.9769
 9766.54212.26999807.479212.34389848.199217.02389868.559225.12529899.052225.0534
9955.599221.0007 9959.91220.17589970.053212.4899 9990.34208.989110020.75209.1994
10051.14213.4909 10071.4221.018110091.66224.175210101.79228.030410111.92228.1411
10122.05 231.44610132.18237.711210244.02 259.70510254.26263.632110280.92267.2469
#Mann= 3 , 0 , 0
9314.543    0.04       09314.543    0.04       010280.92    0.04       0
#XS Ineff= 2 , 0
       0                               0
Bank Sta=9314.543,10280.92
Exp/Cntr=0.3,0.1

Type RM Length L Ch R = 1 , 9006.28,227.504500,227.504500,227.504500
XS GIS Cut Line= 6
803415.898840398726188.534013703802889.917844594726412.263659716
802433.626792103726514.978071362802295.444084555726561.553704873
802096.888390154726679.518781289801747.244913965726967.806113571
#Sta/Elev= 30
9114.593323.82769182.095299.71059204.209285.61239237.381274.15259281.512265.7539
9314.399270.29419369.212266.76929380.174263.80169391.073254.11089412.805254.9674
9434.536243.5444    9478229.96419617.468222.29429681.148212.40199806.618212.3704
9827.333224.06619940.041222.33339970.528208.989110031.33209.400210092.17214.4285
10122.76222.495810163.83221.4226 10279.8229.461910356.97228.991410391.12223.0685
10485.59226.871310522.32241.628510610.34246.818110843.89269.920910985.51295.4374
#Mann= 3 , 0 , 0
9114.593  0.0458       09114.593  0.0458       010985.51  0.0458       0
#XS Ineff= 2 , 0
       0                10225.23       0
Bank Sta=9114.593,10985.51
Exp/Cntr=0.3,0.1

Type RM Length L Ch R = 1 ,8778.775,499.752800,499.752800,499.752800
XS GIS Cut Line= 6
802930.036440392726021.146981109802669.001876321726189.831896097
802439.305645441726313.172160703802347.507127466726372.379964458
802197.662017542726495.942211574 801730.86619629726946.145585565
#Sta/Elev= 30
9524.916255.58929542.955249.35939566.888234.18299578.855229.65649614.755228.9886
9638.688 218.3359662.621212.27649769.901212.26999781.658213.93939793.415223.3102
9826.549 220.1029955.139219.73589977.704210.42549988.827208.989110055.88211.6119
10090.06210.7346 10101.6213.136910119.19212.112810192.74220.062210246.93219.9912
10275.45217.1992 10350.5218.1091 10398.7 223.81910459.01224.812610472.81230.8696
10514.22235.661210654.46 241.76110836.58261.482110915.09270.837111048.69290.1371
#Mann= 3 , 0 , 0
9524.916  0.0428       09524.916  0.0428       011048.69  0.0428       0
#XS Ineff= 2 , 0
       0                 10414.3       0
Bank Sta=9524.916,11048.69
Exp/Cntr=0.3,0.1

Type RM Length L Ch R = 1 ,8279.022,499.752800,499.752800,499.752800
XS GIS Cut Line= 6
802581.695994198725012.587754756802352.037843674725299.854907051
  802177.8207542725640.493275121802073.945382327726310.371425122
802010.291071296726490.254552051801664.806007277726945.840263538
#Sta/Elev= 30
8816.321296.15628846.835293.94748860.188 290.7588900.246275.11048926.951274.8008
8965.907262.89498991.757260.71349030.321 250.1769067.915245.64469080.446239.7015
9105.509232.74979238.047228.69939249.906226.15449261.606217.20429273.188213.5172
9497.508212.53049770.245214.88219810.777211.23889901.633208.989110021.87208.9891
10253.62215.2106 10401.2225.150910423.21224.273910548.44 230.61710643.78241.3621
10745.03258.221110796.66264.523810821.36265.288210943.56277.986511014.09292.5813
#Mann= 3 , 0 , 0
8816.321  0.0188       08816.321  0.0188       011014.09  0.0188       0
#XS Ineff= 2 , 0
       0                               0
Bank Sta=8816.321,11014.09
Exp/Cntr=0.3,0.1

Type RM Length L Ch R = 1 ,7779.269,499.752700,499.752700,499.752700
XS GIS Cut Line= 6
801919.947900057725101.746933967801760.253253549725355.571462274
801677.264975756725563.558796585801533.318527907726474.545420125
801464.172661275726666.039636374801338.243384927726887.973527804
#Sta/Elev= 30
8991.546283.81689093.971267.25719105.979263.62299117.986262.54659200.219248.1361
9257.329 239.9499324.374231.69579389.943227.19929411.594222.63399462.139217.4341
9517.533209.3398 9527.95208.989110430.24208.989110524.38220.043410545.59225.5131
10577.64229.096710599.23227.337910616.11222.4873 10641.7 219.18210653.76 221.254
10665.02219.500510720.61231.860910743.35233.175110766.09236.637110793.65243.9355
10800.83247.177710812.89247.570410832.13254.350610847.65258.344410899.33268.0043
#Mann= 3 , 0 , 0
8991.546  0.0194       08991.546  0.0194       010899.33  0.0194       0
#XS Ineff= 2 , 0
       0                10567.72       0
Bank Sta=8991.546,10899.33
Exp/Cntr=0.3,0.1

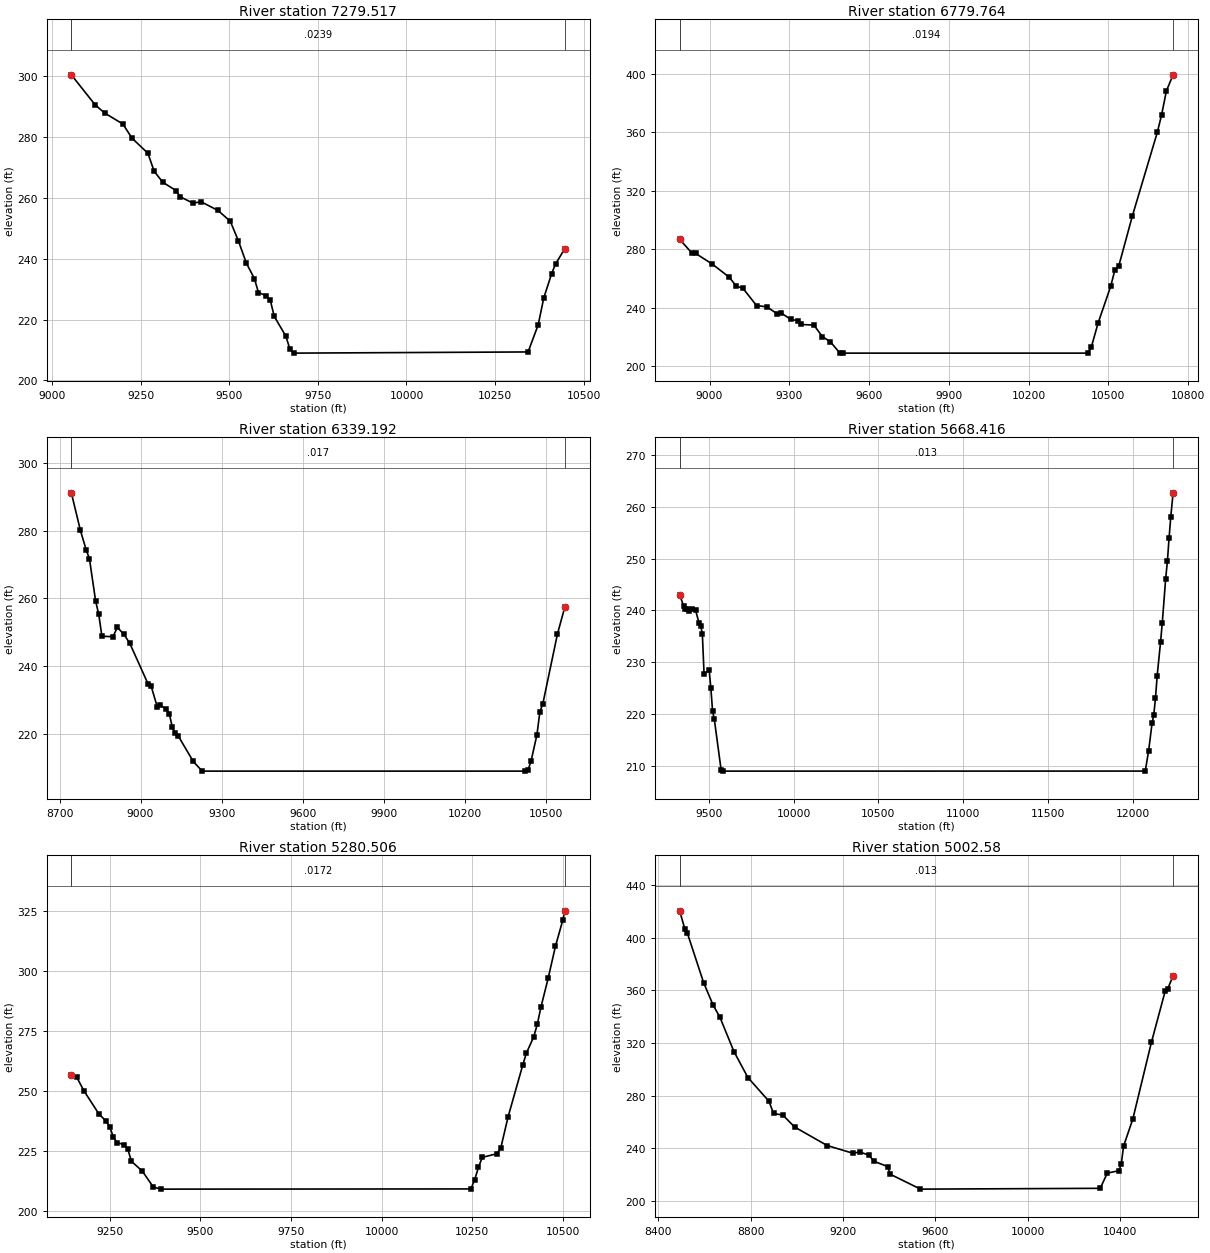
Type RM Length L Ch R = 1 ,7279.517,499.752800,499.752800,499.752800
XS GIS Cut Line= 6
801563.031074017725134.578787431801374.640824884725370.781935021
801251.172427207725580.695453823801172.890543014725758.476044893
801022.333872616726196.248459339800941.940117359726368.215618999
#Sta/Elev= 30
9053.783300.46359121.162290.56839147.676287.92689199.337284.28499225.054 279.653
9269.863274.68239287.812268.72079312.388265.11519349.097262.44079361.174260.3855
9396.747258.30319420.462258.72719467.888255.8713 9502.54 252.3439525.454   245.9
9548.104238.53199570.755233.4641 9582.08228.90089604.612227.84749615.664 226.308
9626.716221.05089659.871214.48729670.923210.25529681.975208.989110343.46209.3779
10372.09218.356610387.58227.079810409.97235.141910421.17238.342710447.17243.3437
#Mann= 3 , 0 , 0
9053.783  0.0239       09053.783  0.0239       010447.17  0.0239       0
#XS Ineff= 2 , 0
       0                               0
Bank Sta=9053.783,10447.17
Exp/Cntr=0.3,0.1

Type RM Length L Ch R = 1 ,6779.764,440.571900,440.571900,440.571900
XS GIS Cut Line= 6
801572.851913959724958.764553323 801371.02867496725115.959725425
801255.986707062725209.866388276 800815.45569706725587.055264845
800599.102153778725757.633515388 800135.15704781726131.569222231
#Sta/Elev= 30
8887.518286.80268935.087 277.1488947.655277.15889011.022269.76029074.655260.8146
9100.109 254.8599125.562253.32129176.942241.47839215.668240.66189254.394235.8572
9267.303236.65619306.249 231.9969332.468231.19849345.577228.56789392.574228.1495
9424.234220.29959454.434216.74119490.029209.07799503.285208.989110422.78208.9891
10435.64213.020910461.01229.4642 10508.7254.737710524.59266.051210538.57268.3109
10590.03 302.74810683.97359.986810700.17371.999210717.99388.228710743.21399.2246
#Mann= 3 , 0 , 0
8887.518  0.0194       08887.518  0.0194       010743.21  0.0194       0
#XS Ineff= 2 , 0
       0                               0
Bank Sta=8887.518,10743.21
Exp/Cntr=0.3,0.1

Type RM Length L Ch R = 1 ,6339.192,670.775800,670.775800,670.775800
XS GIS Cut Line= 6
801632.439902216724787.530194148801438.105195999724899.054143906
801214.031779557725010.486973435801089.712256163725063.100725353
800741.014018625725187.543116942799959.764018625725513.932005838
#Sta/Elev= 30
8743.824291.18558777.295280.10548799.134274.22288810.693271.76968833.812  259.17
8845.371255.2565 8856.93 248.8298897.672248.69658914.291 251.4458938.923 249.346
8960.027246.74339027.922234.72479039.223234.07499061.761227.97379072.925228.3915
9095.254227.34619106.418225.92239117.583221.91689128.747220.16539139.911219.3094
9195.078211.85129228.018208.989110423.65208.989110434.49209.404410445.32211.9982
   10467219.742610477.84226.500810488.67228.837510542.86249.473210570.21257.4707
#Mann= 3 , 0 , 0
8743.824   0.017       08743.824   0.017       010570.21   0.017       0
#XS Ineff= 2 , 0
       0                               0
Bank Sta=8743.824,10570.21
Exp/Cntr=0.3,0.1

Type RM Length L Ch R = 1 ,5668.416,387.910600,387.910600,387.910600
XS GIS Cut Line= 3
801168.328833431724708.260709554800181.204990834724594.111404002
798271.482768625  724411.8197373
#Sta/Elev= 30
9326.758243.06769350.242240.86389360.309240.31149370.375240.33769380.442239.8565
9400.575240.26549420.709240.08479440.842237.62849450.909237.05969460.975235.4741
9471.042227.74049501.242228.46669511.308224.97559521.375220.52989531.442219.0254
9571.708209.22789581.775208.9891 12074.6208.998212094.69212.966512114.78218.2436
12124.83219.832312134.87223.079712144.92227.413712165.01233.934412175.06237.6549
12195.15246.151912205.19249.477712215.24254.042812225.28258.106412238.86262.6951
#Mann= 3 , 0 , 0
9326.758   0.013       09326.758   0.013       012238.86   0.013       0
#XS Ineff= 2 , 0
       0                10848.48       0
Bank Sta=9326.758,12238.86
Exp/Cntr=0.3,0.1

Type RM Length L Ch R = 1 ,5280.506,277.925300,277.925300,277.925300
XS GIS Cut Line= 6
801419.290605575724389.966902882801175.385006696724416.716457397
800919.483514756724393.832208395800705.303007603724326.526225537
800414.008812577 724164.93799822800119.124683158 724118.38577827
#Sta/Elev= 30
9143.809256.60549158.345255.67079178.689249.89779219.204240.46579239.384237.2861
9249.474234.98559259.564230.82189269.641228.33359289.713227.55879299.748225.5479
9309.784220.57569339.867216.45339369.888209.88869389.903208.989110246.65209.0704
10257.12212.951310267.59218.082410277.96222.211210318.94223.752610329.19226.1851
10349.47239.181910389.78260.643510399.83265.648810419.93272.357410429.98277.6717
10440.02284.807310460.04296.879810480.05310.142410500.05320.884810505.93324.8894
#Mann= 3 , 0 , 0
9143.809  0.0172       09143.809  0.0172       010505.93  0.0172       0
#XS Ineff= 2 , 0
       0                               0
Bank Sta=9143.809,10505.93
Exp/Cntr=0.3,0.1

Type RM Length L Ch R = 1 , 5002.58,721.580300,721.580300,721.580300
XS GIS Cut Line= 6
802198.094516442724232.043619151801358.208526103724112.575619502
800818.376817247724029.233844726800618.369172067724006.577597051
800310.689691287723953.461679485 800081.31297576723931.253470091
#Sta/Elev= 30
8492.003420.2862 8515.33406.14418525.431403.44258596.136365.74238636.538348.9704
 8666.84339.43678727.444313.45198788.048293.68488878.954275.76558899.155266.4492
8939.558265.18898990.061256.19969131.471242.08849242.578236.2586 9272.88237.1698
9313.282 234.7559333.484230.17279394.183226.07359404.301 220.3469535.841208.9891
10314.93209.601410345.25221.107810395.78223.006810405.85227.8261 10415.9241.5905
10456.09 262.23310536.46320.324810596.74359.643210606.79360.898610630.59 370.883
#Mann= 3 , 0 , 0
8492.003   0.013       08492.003   0.013       010630.59   0.013       0
#XS Ineff= 2 , 0
       0                               0
Bank Sta=8492.003,10630.59
Exp/Cntr=0.3,0.1

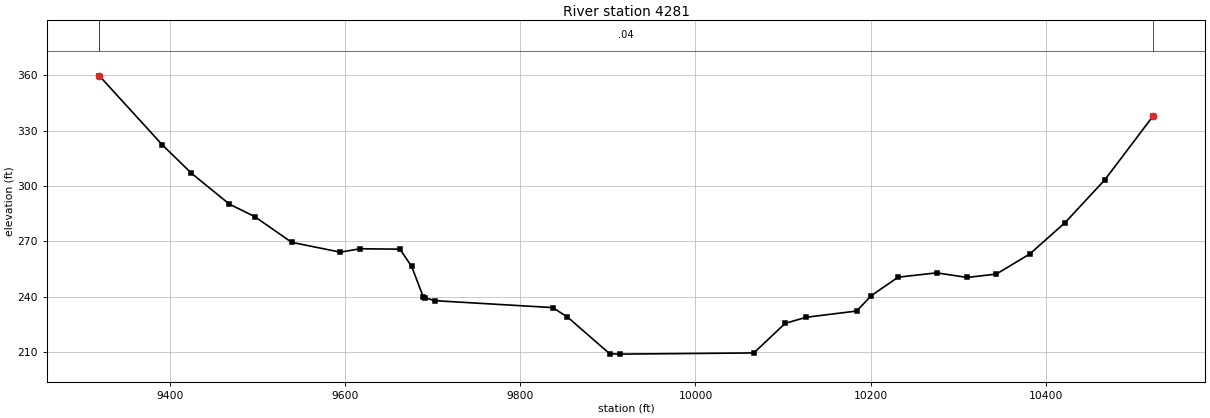
Type RM Length L Ch R = 1 ,    4281,0.000000,0.000000,0.000000
XS GIS Cut Line= 6
800838.352663666722933.764522749800654.865019436723109.273598416
800541.114875782723236.946237621800253.648654094723651.358036519
800141.139398551723752.205280464800038.416248673 723818.59309246
#Sta/Elev= 30
9318.813359.63999390.957322.17519424.115306.87539467.456290.16829496.331283.4383
9538.588 269.5099594.212 264.1919616.732266.02039662.359265.79719675.699256.4327
9688.812240.13249691.427239.42099701.924237.92639836.864234.1835 9853.74 229.059
9901.932209.20879913.731208.9891 10066.7209.6365 10102.5225.658810126.61228.9478
10184.14232.317310200.99240.685610231.48250.630710275.46252.981210310.49250.4986
 10343.8252.329710382.33263.315910422.28280.177210467.73303.336410522.49337.6306
#Mann= 3 , 0 , 0
9318.813    0.04       09318.813    0.04       010522.49    0.04       0
#XS Ineff= 2 , 0
       0                               0
Bank Sta=9318.813,10522.49
Exp/Cntr=0.3,0.1